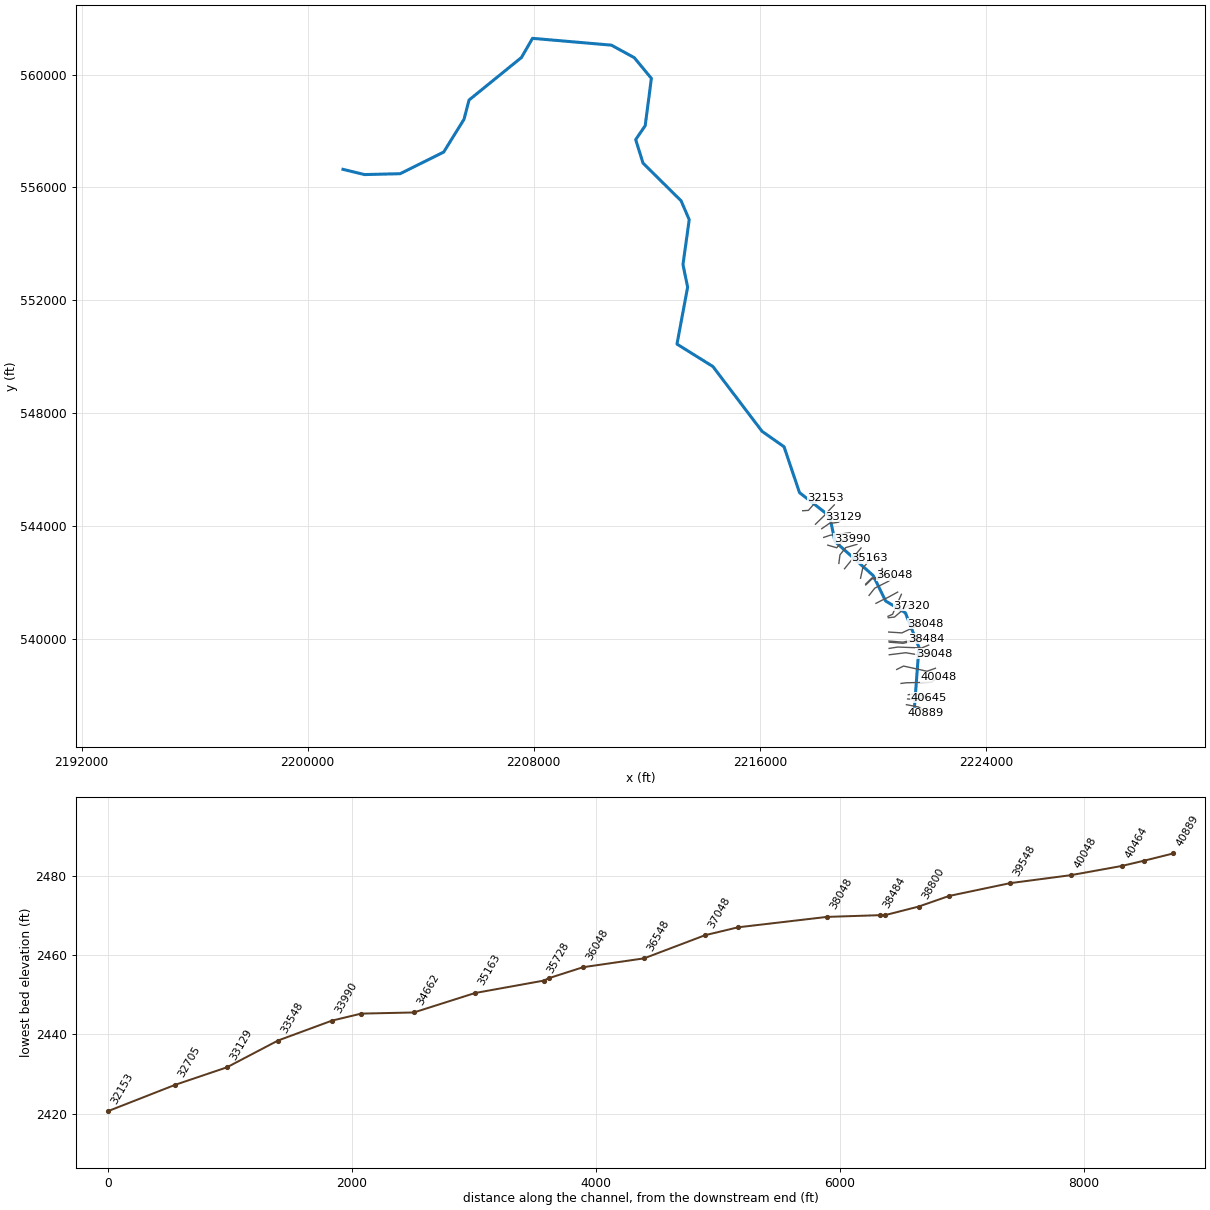
--- ELKRIV.prj (project) ---

Proj Title=ELKRIV
Current Plan=p01
Default Exp/Contr=0,0
English Units
Geom File=g01
Flow File=f01
Plan File=p01
Background Map Layer=Inundation Boundary (P100yr Value_0)
BEGIN DESCRIPTION:
----------MODEL BY WOOD PLC 2022----------
AFH study
Randolph County, WV
HEC-RAS Version: RAS 6.2
Vertical Datum: NAVD88
Projection: NAD 1983 StatePlane West Virginia S FIPS 4702 (US Feet)
Terrain: 1-meter LIDAR (FEMA Region III 3DEP collected 2016-2018)
Land Use: 2019 NLCD
Hydrologic Method:
WV SIR2010-5033 regression equations
Additional Model Notes:
Elk River extends outside of the county boundary.
3 shared XS from Pocahontas County on the upstream extent
END DESCRIPTION:
DSS Export Rating Curves= 0
DSS Export Rating Curve Sorted= 0
DSS Export Volume Flow Curves= 0
DXF OffsetX= 0
DXF OffsetY= 0
DXF ScaleX= 0
DXF ScaleY= 0

--- ELKRIV.p01 (plan) ---

Plan Title=Floodplain
Program Version=6.20
Short Identifier=Floodplain
Geom File=g01
Flow File=f01
Subcritical Flow
K Sum by GR= 0
Std Step Tol= 0.01
Critical Tol= 0.01
Num of Std Step Trials= 20
Max Error Tol= 0.3
Flow Tol Ratio= 0.001
Split Flow NTrial= 30
Split Flow Tol= 0.02
Split Flow Ratio= 0.02
Log Output Level= 0
Friction Slope Method= 1
Unsteady Friction Slope Method= 2
Unsteady Bridges Friction Slope Method= 1
Parabolic Critical Depth
Global Vel Dist= 0 , 0 , 0
Global Log Level= 0
CheckData=True
Encroach Param=-1 ,0,0, 0
Mapping Interval=1HOUR
Computation Time Step Use Courant=        0
Computation Time Step Use Time Series=    0
Computation Time Step Count To Double=0
Computation Time Step Max Doubling=0
Computation Time Step Max Halving=0
Computation Time Step Residence Courant=0
Run HTab= 0
Run UNet= 0
Run Sediment= 0
Run PostProcess= 0
Run WQNet= 0
Run RASMapper= 0
UNET Theta= 0
UNET Theta Warmup= 0
UNET ZTol= 0
UNET ZSATol= 0
UNET MxIter= 0
UNET Max Iter WO Improvement= 0
UNET MaxInSteps= 0
UNET DtIC= 0
UNET DtMin= 0
UNET MaxCRTS= 0
UNET WFStab= 0
UNET SFStab= 0
UNET WFX= 1
UNET SFX= 1
UNET Gravity=32.174
UNET 1D Methodology=Finite Difference
UNET DSS MLevel= 1
UNET Pardiso=0
UNET DZMax Abort= 0
UNET Use Existing IB Tables= 0
UNET Froude Reduction=False
UNET Froude Limit= 0
UNET Froude Power= 0
UNET D1 Cores= 0
UNET WindReference=Eulerian
UNET WindDragFormulation=Hsu (1988)
UNET D2 Coriolis=0
UNET D2 Cores= 0
UNET D2 Theta= 1
UNET D2 Theta Warmup= 1
UNET D2 Z Tol= 0.01
UNET D2 Volume Tol= 0.01
UNET D2 Max Iterations= 20
UNET D2 Equation= 0
UNET D2 RampUpFraction=0.1
UNET D2 TimeSlices= 1
UNET D2 Turbulence Formulation=Non-Conservative (original)
UNET D2 Eddy Viscosity=0.3
UNET D2 Transverse Eddy Viscosity=0.1
UNET D2 Smagorinsky Mixing=0
UNET D2 BCVolumeCheck=0
UNET D2 Cores=0
UNET D2 SolverType=PARDISO (Direct)
UNET D2 Minimum Iterations= 2147483647
UNET D2 Maximum Iterations= 2147483647
UNET D2 Restart Number= 10
UNET D2 Relaxation Coeff=1.3
UNET D2 SOR Precondition Iterations= 10
UNET D2 ILUT Maximum Fill= 8
UNET D2 ILUT Tolerance=1E-08
UNET D1D2 MaxIter= 0
UNET D1D2 ZTol=0.01
UNET D1D2 QTol=0.1
UNET D1D2 MinQTol=1
Write IC File= 0
Write IC File at Fixed DateTime=0
Write IC File at Sim End=0
Echo Input=False
Echo Parameters=False
Echo Output=False
Write Detailed= 0
HDF Write Warmup=0
HDF Write Time Slices=0
HDF Flush=0
HDF Compression= 1
HDF Chunk Size= 1
HDF Spatial Parts= 1
HDF Use Max Rows=0
HDF Fixed Rows= 1
Calibration Method= 0
Calibration Iterations= 20
Calibration Max Change=0.05
Calibration Tolerance=0.2
Calibration Maximum=1.5
Calibration Minimum=0.5
Calibration Optimization Method= 1
WQ AD Non Conservative
WQ ULTIMATE=-1
WQ Max Comp Step=1HOUR
WQ Output Interval=15MIN
WQ Output Selected Increments= 0
WQ Output face flow=0
WQ Output face velocity=0
WQ Output face area=0
WQ Output face dispersion=0
WQ Output cell volume=0
WQ Output cell surface area=0
WQ Output cell continuity=0
WQ Output cumulative cell continuity=0
WQ Output face conc=0
WQ Output face dconc_dx=0
WQ Output face courant=0
WQ Output face peclet=0
WQ Output face adv mass=0
WQ Output face disp mass=0
WQ Output cell mass=0
WQ Output cell source sink temp=0
WQ Output nsm pathways=0
WQ Output nsm derived pathways=0
WQ Create Restart=0
WQ Fixed Restart=0
WQ System Summary=0
WQ Write To DSS=0
Sorting and Armoring Iterations= 10
XS Update Threshold= 0.02
Bed Roughness Predictor= 0
Hydraulics Update Threshold= 0.02
Energy Slope Method= 1
Volume Change Method= 1
Sediment Retention Method= 0
Sediment TS Multiplier= 1
Warm Up Method= 0
XS Weighting Method= 0
Number of US Weighted Cross Sections= 1
Number of DS Weighted Cross Sections= 1
Upstream XS Weight=0
Main XS Weight=1
Downstream XS Weight=0
Number of DS XS's Weighted with US Boundary= 1
Upstream Boundary Weight= 1
Weight of XSs Associated with US Boundary= 0
Number of US XS's Weighted with DS Boundary= 1
Downstream Boundary Weight= 0.5
Weight of XSs Associated with DS Boundary= 0.5
Percentile Method= 0
Sediment Output Level= 3
Mass or Volume Output= 0
Output Increment Type= 1
Profile and TS Output Increment= 1
Transport Output Increment 1
XS Output Flag= 0
XS Output Increment= 10
Read HDF5 Sediment Hotstart= 0
Sediment Hotstart Type= 0
Write Gradation File= 0
Read Gradation Hotstart= 0
Write HDF5 File= 1
Write Binary Output= 1
Write DSS Sediment File= 0
DSS Sediment Output Type= 1
SV Curve= 0
Specific Gage Flag= 0
Subcell Erosion Methods= 0
Subcell Deposition Methods= 0
Advection Scheme= 1
Matrix Solver= 0
Implicit Weighting Factor= 1
Maximum Outer Loop Convergence Iterations= 5
Convergence Maximum Absolute= 0.001
Convergence RMSE= 0.0001
Grain Fractions Max Abs Error= 0.001
Max Subgrid Regions= 1
Max Subgrid Length Scale= 3.402823E+38
Initial Layer Thickness= 3.402823E+38
Min Layer Thickness= 3.402823E+38
Max Layer Thickness= 3.402823E+38
Number of Layers= 5

--- ELKRIV.f01 (steady flow) ---

Flow Title=Flow
Program Version=6.20
Number of Profiles= 6
Profile Names=01pct,10pct,04pct,02pct,0_2pct,01plus
River Rch & RM=ELKRIV,Main            ,40889
   10600    6240    7860    9160   14000   15600
River Rch & RM=ELKRIV,Main            ,16554
   11900    7080    8900   10400   15700   17600
Boundary for River Rch & Prof#=ELKRIV,Main            , 1
Up Type= 0
Dn Type= 1
Dn Known WS=2493.5
Boundary for River Rch & Prof#=ELKRIV,Main            , 2
Up Type= 0
Dn Type= 1
Dn Known WS=2490.6
Boundary for River Rch & Prof#=ELKRIV,Main            , 3
Up Type= 0
Dn Type= 1
Dn Known WS=2491.7
Boundary for River Rch & Prof#=ELKRIV,Main            , 4
Up Type= 0
Dn Type= 1
Dn Known WS=2492.6
Boundary for River Rch & Prof#=ELKRIV,Main            , 5
Up Type= 0
Dn Type= 1
Dn Known WS=2495.3
Boundary for River Rch & Prof#=ELKRIV,Main            , 6
Up Type= 0
Dn Type= 1
Dn Known WS=2496.2
DSS Import GetInterval= 0
DSS Import GetPeak= 0
DSS Import FillOption= 0

--- ELKRIV.g01 (geometry) ---

Geom Title=Geometry
Program Version=6.20

River Reach=ELKRIV          ,Main
Reach XY= 30
2221475.37003061 537631.143747272221631.49500002      539714.706
2221151.52299999       540940.25     2220450.903541358.458000004
2220015.38300003542255.8190000212218660.09800002543462.853000015
2218472.90799998544359.2430000012217404.67700002545195.357000008
     2216857.983546818.8520000282216079.12799999547366.015000016
2214338.77100001549661.8460000162213069.49300003550455.101000011
2213446.39400002552472.8410000212213281.06000003553270.364999995
2213502.80100003554859.8400000042213214.77599999555528.982999995
2211867.46299998556862.8129999942211608.18700004557695.366000026
2211944.38599999558187.0990000072212163.67200001559863.482000008
2211558.74900003560596.1720000212210751.03099999561039.454999998
2207957.21000004561281.2629999972207566.74699999560603.313999996
     2205711.877559097.3330000042205533.22799999558414.532000005
2204814.04000001557253.6449999962203274.12799999556487.996000022
     2202013.263556457.0660000152201250.95299999556642.247000009

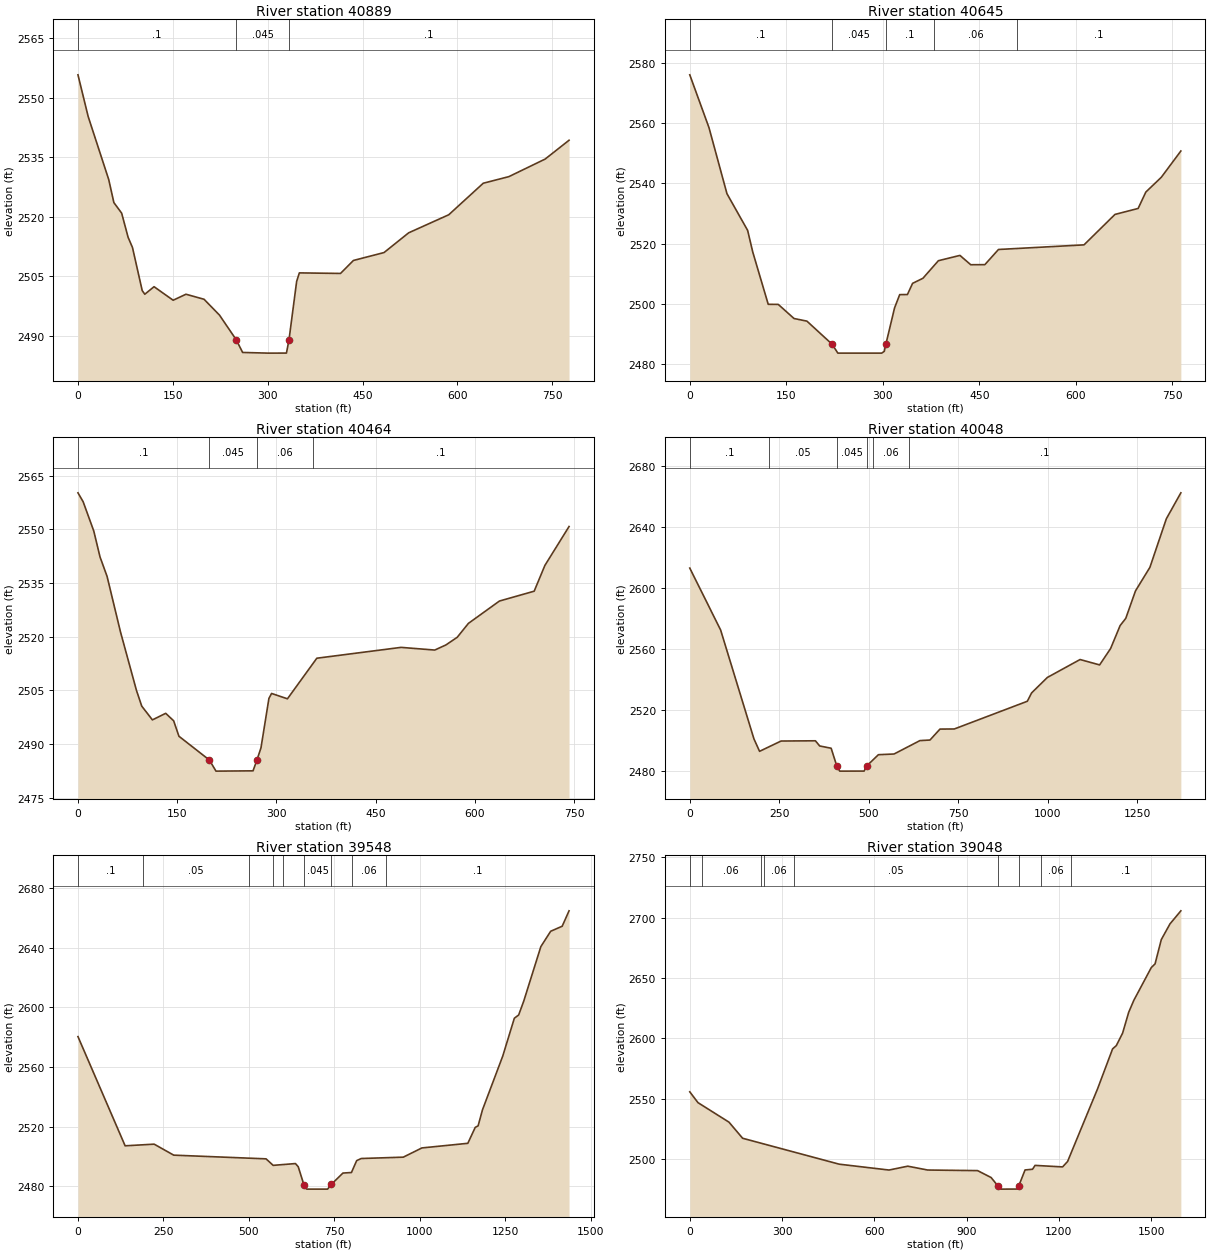
Type RM Length L Ch R = 1 ,40889   ,244,244,244
XS GIS Cut Line= 4
2221188.40568485537686.2932469452221618.38619091537603.658556856
2221776.65263125537493.0121074152221866.29026118537378.163894071
#Sta/Elev= 30
       0 2555.75    16.1 2545.26    48.6 2529.38    56.8 2523.55    69.1 2520.89
    79.3  2514.8    86.2 2512.24   101.6 2501.38   105.7 2500.46   120.3 2502.36
   150.5 2498.95   170.8 2500.46   199.4 2499.19   223.8  2495.2   250.2 2489.01
   260.4 2485.79   300.8 2485.62   329.7 2485.63   333.8 2489.05   345.8 2503.67
   350.1 2505.84   415.2  2505.7   435.6 2508.97     484 2510.96     523 2515.94
   586.4 2520.49   640.9 2528.43   681.5  2530.1   738.8 2534.52   776.6 2539.26
#Mann= 3 ,-1,0
       0      .1       0   250.2    .045       0   333.8      .1       0
Bank Sta=250.2,333.8
XS Rating Curve= 0 ,0
Exp/Cntr=0.3,0.1

Type RM Length L Ch R = 1 ,40645   ,181.1,181.1,181.1
XS GIS Cut Line= 4
2221230.42332388537887.9779142812221628.19030668537866.969094767
 2221761.2461636537920.1914375372221982.53906249 537929.99555331
#Sta/Elev= 30
       0    2576    29.8 2558.52    57.8 2536.59    89.9 2524.44    97.9 2517.24
   121.9 2499.94   137.5 2499.91     162 2495.23     182 2494.37   221.2  2486.7
   230.1 2483.76   298.2 2483.76   302.2 2484.35   304.9 2486.87   318.2 2498.74
   326.2 2503.15   338.2 2503.18   346.2 2506.88   362.3 2508.57   386.3 2514.39
   419.8 2516.15   436.6 2513.06   458.5 2513.08   479.7 2518.11   612.6 2519.64
   660.7 2529.73   696.7 2531.71   708.7 2537.15   732.7 2542.04   763.1 2550.75
#Mann= 5 ,-1,0
       0      .1       0   221.2    .045       0   304.9      .1       0
     380     .06       0  508.32      .1       0
Bank Sta=221.2,304.9
XS Rating Curve= 0 ,0
Exp/Cntr=0.3,0.1

Type RM Length L Ch R = 1 ,40464   ,415.1,415.1,415.1
XS GIS Cut Line= 5
2221256.44686432538039.8106316492221382.65619828538055.044704613
2221610.86339018538055.401256223 2221881.4716721537959.484533329
2221980.38013938537946.746321635
#Sta/Elev= 30
       0 2560.17     7.8 2557.69    23.9  2549.5    33.3 2542.28      44 2536.83
    64.2 2521.37    88.4    2505    96.4  2500.6   112.5 2496.76   132.6 2498.59
   144.6 2496.51   152.6 2492.19   198.6 2485.55   208.6 2482.45   264.6 2482.53
   270.7 2485.66   276.6 2488.96   288.6 2502.75   292.6 2504.14   316.6 2502.65
     361 2513.98   488.3 2517.01   539.2 2516.26   556.2  2517.7   573.2 2519.83
   590.1 2523.71     637 2529.95   689.5  2532.7   705.7  2539.9   742.2 2550.76
#Mann= 4 ,-1,0
       0      .1       0   198.6    .045       0   270.7     .06       0
  355.33      .1       0
Bank Sta=198.6,270.7
XS Rating Curve= 0 ,0
Exp/Cntr=0.3,0.1

Type RM Length L Ch R = 1 ,40048   ,500,500,500
XS GIS Cut Line= 5
2220998.64821922538438.8472455662221188.74824585538462.380369985
     2221449.947      538467.266 2222069.0704491538478.415900747
 2222313.4932097538652.444191875
#Sta/Elev= 30
       0 2613.13    86.2 2572.57   179.2  2501.3     195 2493.11     255 2499.85
     351 2500.01     363 2496.62     395 2495.13     411 2483.31     419 2480.14
     487 2480.17     495 2483.66     527  2490.9   570.8 2491.36   643.1 2500.14
   671.1  2500.5   699.1 2507.68   739.1 2507.75   943.1  2525.9   955.1 2531.38
   999.1  2541.5  1090.5 2553.24  1145.1 2549.71  1175.8 2560.44  1202.4 2575.47
  1218.2 2580.22  1245.4 2598.23  1285.6 2613.61  1331.5 2645.42  1372.1 2662.43
#Mann= 6 ,-1,0
       0      .1       0  221.55     .05       0     411    .045       0
     495      .1       0   512.8     .06       0   612.8      .1       0
Bank Sta=411,495
XS Rating Curve= 0 ,0
Exp/Cntr=0.3,0.1

Type RM Length L Ch R = 1 ,39548   ,500,500,500
XS GIS Cut Line= 5
2220844.64409555538932.6820861672221086.36914333539053.249076708
     2221508.765      538960.8382221915.49035244538869.657021573
2222215.11422973538975.389906872
#Sta/Elev= 30
       0 2580.42     138 2507.18     223 2508.28   280.2 2500.91   550.4 2498.43
   571.2 2494.06   636.4 2495.27   644.6 2493.13     661 2481.18   669.2 2478.12
   730.6 2478.12   741.9 2481.41   775.4  2488.9   800.3 2489.26   815.6 2497.24
     829 2498.66     952 2499.56  1006.5 2505.75  1140.9 2508.85  1162.5 2519.52
    1171 2520.58  1183.7 2531.26  1243.1 2567.38    1277 2592.75  1289.7 2594.95
  1304.5 2604.22  1354.6 2640.79  1383.4 2651.11    1417 2654.46  1437.1  2664.8
#Mann= 9 ,-1,0
       0      .1       0     190     .05       0  500.12      .1       0
  570.12     .05       0  600.12      .1       0     661    .045       0
   741.9      .1       0  802.51     .06       0  902.51      .1       0
Bank Sta=661,741.9
XS Rating Curve= 0 ,0
Exp/Cntr=0.3,0.1

Type RM Length L Ch R = 1 ,39048   ,248.7,248.7,248.7
XS GIS Cut Line= 5
2220581.65570494539453.5675073942221163.23936814539525.878969159
     2221602.998      539451.7222221788.88866558539417.339298414
2222158.71860336 539483.38566408
#Sta/Elev= 30
       0 2555.55    26.7 2546.57   127.4 2530.42   171.8 2517.06   485.9 2495.57
   647.9 2490.71   708.7 2493.91   773.6 2490.72   935.9 2490.23   979.7 2484.52
 1001.962477.562  1012.9 2474.89  1062.7 2474.94  1069.8 2477.65  1090.2 2490.79
  1114.6 2491.37  1122.7 2494.56  1212.2 2493.31  1228.5 2497.81    1326 2558.05
  1374.8 2591.13  1386.9 2593.87  1407.3 2604.16  1427.2 2621.49  1443.8 2631.36
  1500.7 2658.57  1512.9 2661.61  1533.2 2681.73  1561.4 2694.75  1596.8 2705.59
#Mann= 9 ,-1,0
       0      .1       0      40     .06       0     230      .1       0
     240     .06       0     340     .05       0 1001.96    .045       0
  1069.8      .1       0 1142.03     .06       0 1241.07      .1       0
Bank Sta=1001.96,1069.8
XS Rating Curve= 0 ,0
Exp/Cntr=0.3,0.1

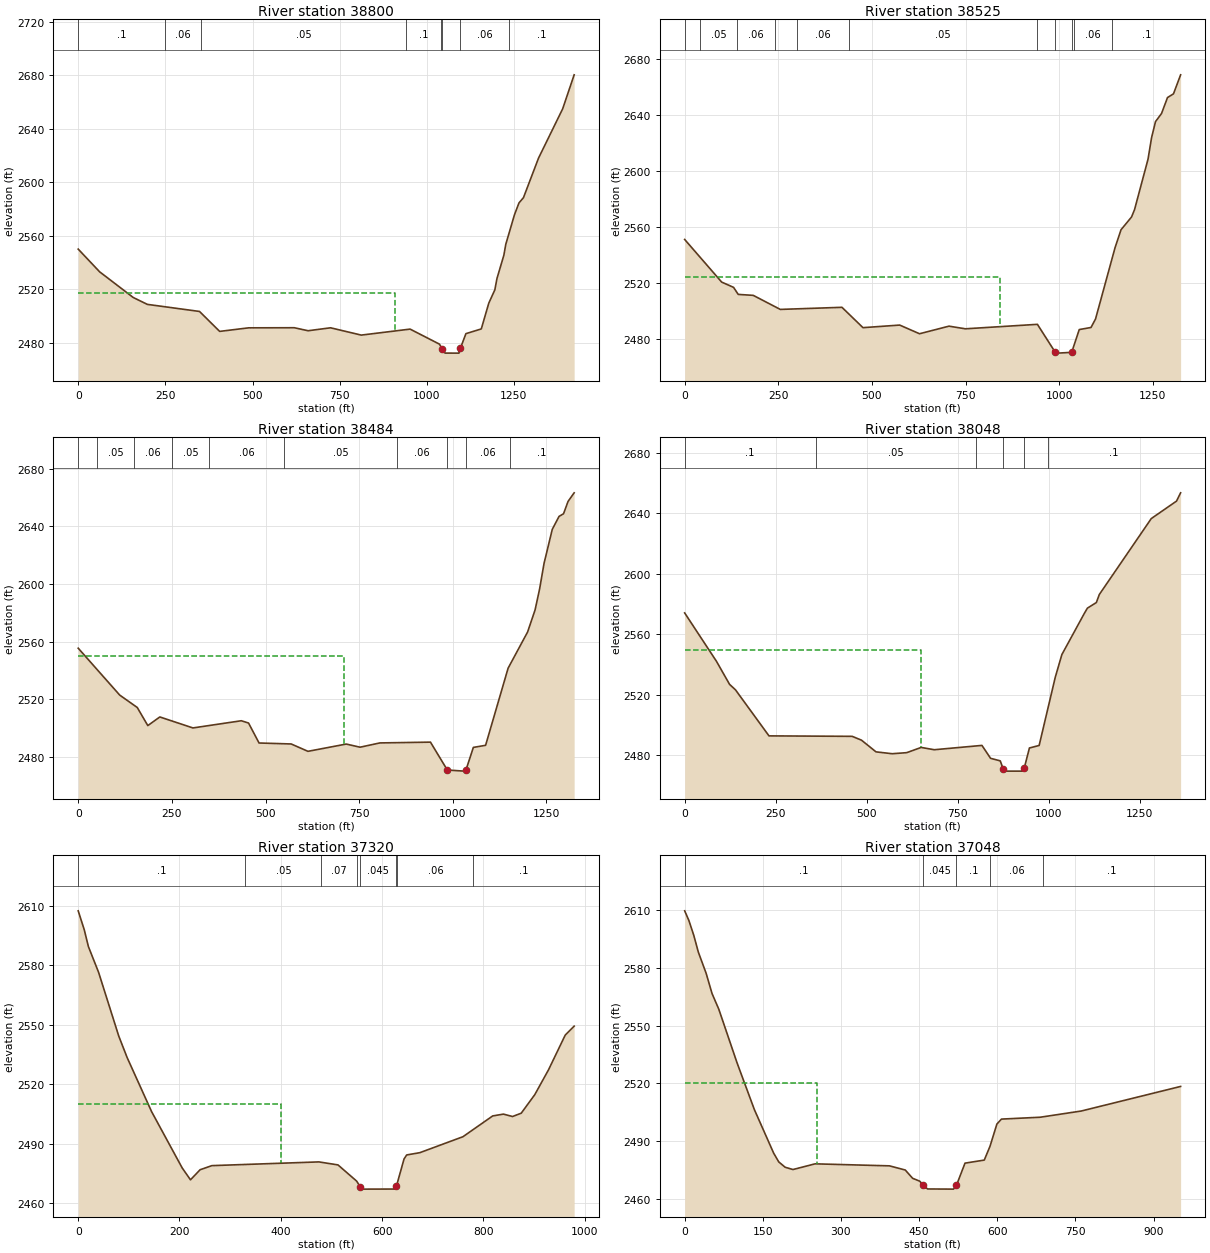
Type RM Length L Ch R = 1 ,38800   ,274.3,274.3,274.3
XS GIS Cut Line= 4
2220576.27442678539678.8990594122220883.45148702539726.949853555
2221728.67101285539694.5725346722221974.63415259539795.824356368
#Sta/Elev= 30
       0    2550    61.4 2533.04   157.8 2513.83   198.3 2508.68     348 2503.38
   405.8 2488.47   488.8 2491.13   619.9 2491.21   659.5 2488.96   723.9 2491.16
     812  2485.7   952.1 2490.18  1036.2 2478.95  1044.2  2475.4  1052.2 2472.24
  1092.2 2472.22  1096.5 2475.92  1112.2 2486.79  1156.3 2490.31  1177.8 2509.58
  1195.2 2519.56  1201.3 2528.04  1221.1 2545.49  1226.6 2553.61  1251.4 2575.62
  1264.4 2584.53  1277.3 2588.49  1320.6  2618.1  1389.8 2654.94  1422.7 2680.34
#Mann= 8 ,-1,0
       0      .1       0     250     .06       0  350.91     .05       0
  940.91      .1       0 1040.91     .06       0  1044.2    .045       0
  1096.5     .06       0 1236.75      .1       0
#XS Ineff= 2 , 0
          909.89 2517.21
Permanent Ineff=
       F       F
Bank Sta=1044.2,1096.5
XS Rating Curve= 0 ,0
Exp/Cntr(USF)=0,0
Exp/Cntr=0.3,0.1

Type RM Length L Ch R = 1 ,38525   ,41.4,41.4,41.4
BEGIN DESCRIPTION:
structure
END DESCRIPTION:
XS GIS Cut Line= 4
 2220581.6644383539899.1361781072221070.05399493 539860.01272711
2221658.96014314539983.7080914242221891.17273977539977.735357445
#Sta/Elev= 30
       0 2551.19    98.8 2520.77   130.5 2517.01     143 2511.98   183.1  2511.3
   255.3 2501.27   419.9 2502.77     476 2488.25     574 2490.09     627  2483.9
   705.5 2489.32   749.4 2487.43   941.7 2490.62   989.3 2470.68   994.9 2470.07
  1033.2 2470.61  1053.4 2486.89  1084.8 2488.38  1096.9 2494.47  1148.9 2545.29
  1164.9 2558.13    1193 2567.24    1201  2572.5    1237  2608.5  1246.4 2623.78
    1257 2635.34    1273 2641.08    1289 2652.48    1305 2655.16    1324 2668.71
#Mann= 11 ,-1,0
       0      .1       0      40     .05       0     140     .06       0
     240     .05       0     300     .06       0     440     .05       0
  939.95      .1       0   989.3    .045       0  1033.2      .1       0
 1039.95     .06       0 1141.71      .1       0
#XS Ineff= 2 , 0
          840.47 2524.12
Permanent Ineff=
       F       F
Bank Sta=989.3,1033.2
XS Rating Curve= 0 ,0
Exp/Cntr=0.3,0.1

Type RM Length L Ch R = 1 ,38484   ,435.6,435.6,435.6
BEGIN DESCRIPTION:
structure
END DESCRIPTION:
XS GIS Cut Line= 4
2220570.94806285539939.1439797782221059.33761948539900.020528781
2221648.24376769540023.7158930952221880.45636432540017.743159116
#Sta/Elev= 30
       0 2555.45   110.7  2522.9   157.7 2514.24   185.8 2501.69   217.9 2507.69
   306.2 2500.06   435.4 2505.05   454.7 2503.48   482.8  2489.6   568.5 2488.92
   613.4 2483.81   715.6 2488.86   752.4 2486.68   805.5 2489.65   940.4 2490.19
   985.4 2470.83  1030.3 2470.06 1035.242470.858  1054.9 2486.53  1087.6 2487.99
  1147.7 2541.56  1199.7 2566.68  1219.7 2582.04  1231.7 2596.48  1243.7 2614.43
  1265.6    2638  1283.7 2646.99  1295.7 2648.84  1307.7 2657.38    1324 2663.36
#Mann= 10 ,-1,0
       0      .1       0      50     .05       0     150     .06       0
     250     .05       0     350     .06       0  549.95     .05       0
  849.95     .06       0   985.4    .045       0 1035.24     .06       0
 1151.71      .1       0
#XS Ineff= 2 , 0
           710.5    2550
Permanent Ineff=
       F       F
Bank Sta=985.4,1035.24
XS Rating Curve= 0 ,0
Exp/Cntr=0.3,0.1

Type RM Length L Ch R = 1 ,38048   ,728.7,728.7,728.7
XS GIS Cut Line= 6
 2220561.1564805540258.1610150942221030.38347942540228.149214329
     2221425.207      540416.5362221487.64692063540447.414482277
2221593.78973433540499.3223351422221855.29819301540550.423308176
#Sta/Elev= 30
       0 2574.17    87.2 2542.24   123.3 2526.96   139.4 2523.39   231.5 2492.92
     460 2492.61   485.5 2490.09   525.4 2482.36   569.7 2481.12   609.6 2481.82
   649.5 2485.28   685.3 2483.76   816.3 2486.62     840 2478.09   866.6  2476.4
   874.4 2471.28   879.9 2469.62   928.8 2469.62  932.542471.634   946.7 2484.91
   973.4 2486.58  1017.7 2531.67  1035.8 2546.66  1097.9 2574.05    1106 2577.35
  1130.5 2581.05  1138.7 2586.38  1281.3 2636.53  1350.6 2648.08  1361.9 2653.56
#Mann= 6 ,-1,0
       0      .1       0     360     .05       0  800.19      .1       0
   874.4    .045       0  932.54     .06       0  997.31      .1       0
#XS Ineff= 2 , 0
             650    2550
Permanent Ineff=
       F       F
Bank Sta=874.4,932.54
XS Rating Curve= 0 ,0
Exp/Cntr=0.3,0.1

Type RM Length L Ch R = 1 ,37320   ,271.3,271.3,271.3
XS GIS Cut Line= 4
2220548.24305323 540764.467284412220767.09073031540789.530990044
2221242.59480414541199.4019420642221373.78790817541194.200389166
#Sta/Elev= 30
       0 2607.47      12 2597.87    20.1 2589.43    40.2 2576.47    80.1 2544.22
    96.6 2533.42   144.9 2506.12   205.3  2477.7   221.7  2471.7   240.7 2476.79
     264 2478.86   475.2 2480.74   512.9 2479.23   549.8 2471.05   556.7 2468.22
     564    2467   624.1 2467.04   628.3 2468.43   643.4 2482.21   648.6 2484.25
   674.6  2485.4   759.7 2493.45   818.5 2503.95   839.6 2504.86   857.6 2503.65
   874.8 2505.32   901.6  2514.7   928.7 2527.23   961.7 2544.76   979.3 2549.26
#Mann= 8 ,-1,0
       0      .1       0  330.28     .05       0  480.28     .07       0
  550.28      .1       0   556.7    .045       0   628.3      .1       0
  630.28     .06       0  780.28      .1       0
#XS Ineff= 2 , 0
             400    2510
Permanent Ineff=
       F       F
Bank Sta=556.7,628.3
XS Rating Curve= 0 ,0
Exp/Cntr=0.3,0.1

Type RM Length L Ch R = 1 ,37048   ,500,500,500
XS GIS Cut Line= 4
2220536.25861843540814.5910573342220698.19359842540886.955855049
     2220826.715      541179.608     2221010.854      541595.683
#Sta/Elev= 30
       0 2609.69       8 2604.71    17.4 2597.02    26.2 2588.25    41.3 2577.12
    52.5 2566.71    65.5 2558.55   100.7 2530.54   133.8 2506.34   170.8 2483.72
   180.6 2479.15   192.9 2476.37   207.9 2475.19   250.4 2478.15   393.1  2477.1
   423.4 2474.94   437.6 2470.62   450.9 2469.18   458.3 2467.12   466.1 2465.09
   516.2    2465  521.762467.007   538.1  2478.5   575.1  2480.1   586.2 2487.34
   599.3 2498.83   608.1 2501.41   682.4 2502.38   761.2  2505.6     952 2518.39
#Mann= 5 ,-1,0
       0      .1       0   458.3    .045       0  521.76      .1       0
     587     .06       0     687      .1       0
#XS Ineff= 2 , 0
          253.82  2520.3
Permanent Ineff=
       F       F
Bank Sta=458.3,521.76
XS Rating Curve= 0 ,0
Exp/Cntr=0.3,0.1

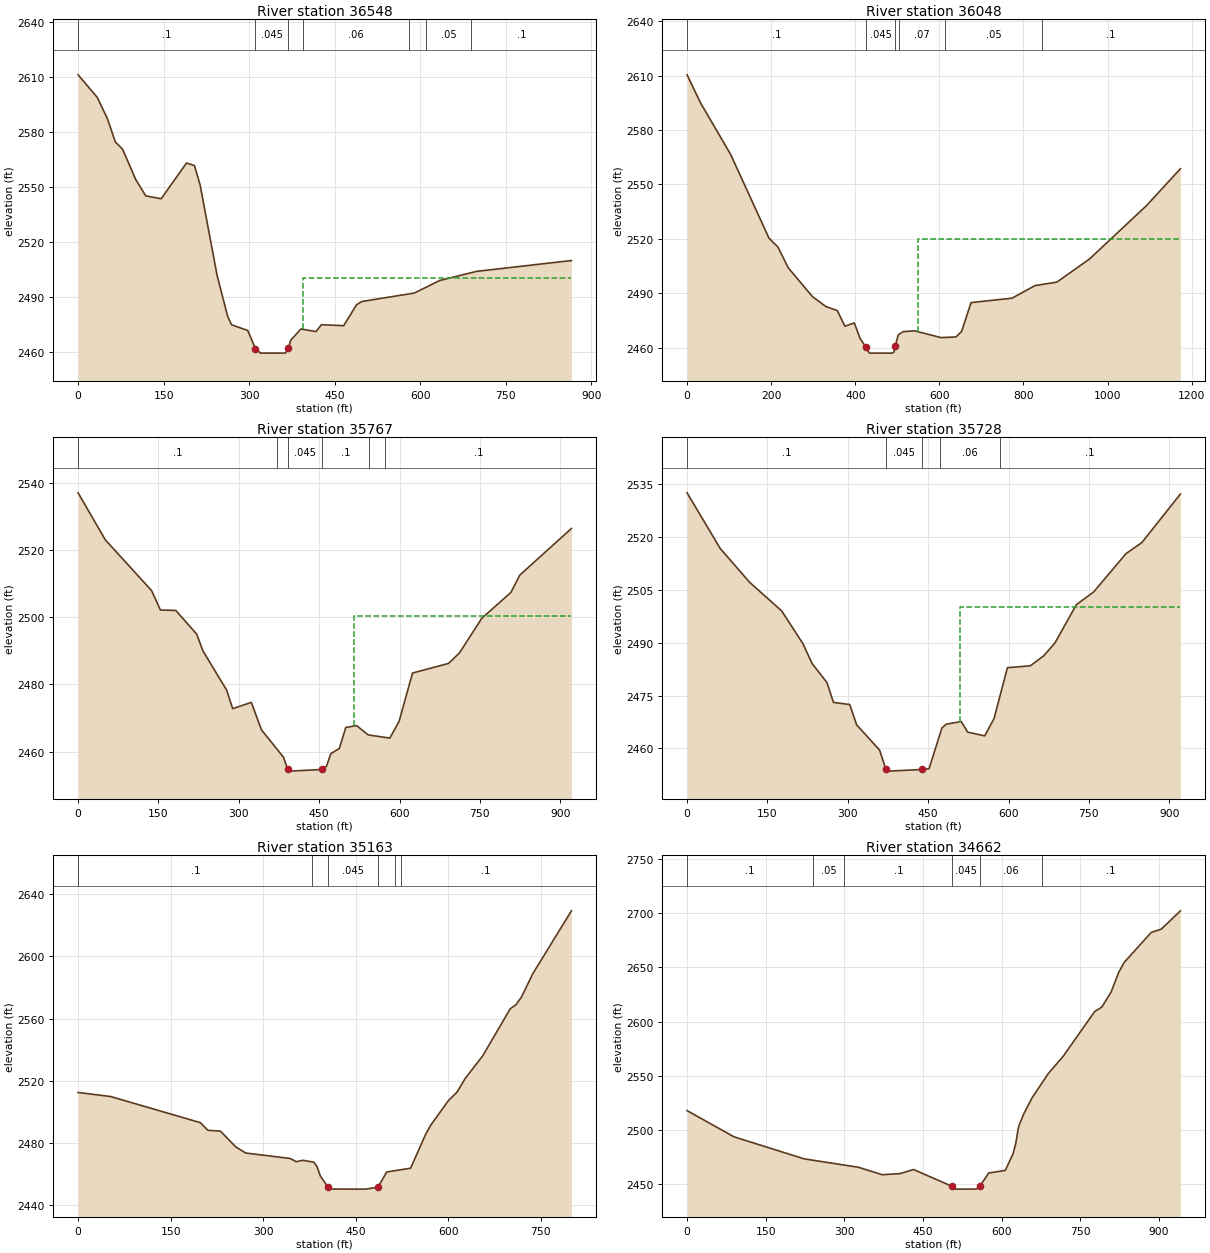
Type RM Length L Ch R = 1 ,36548   ,500,500,500
XS GIS Cut Line= 5
2220110.40150898541275.0608165152220344.65163565541394.549358459
     2220408.922      541424.9372220531.58296801541482.512946777
2220878.66600514541672.640197602
#Sta/Elev= 30
       0 2611.35    33.4 2599.12    51.4 2587.44    65.3  2574.7    78.3 2570.54
     101 2554.16   118.7 2545.17   145.7 2543.59   190.2 2563.13   204.1 2561.73
     214 2551.23   243.8 2501.71   262.4 2479.21   269.1 2474.68   297.6 2471.54
   311.1 2461.57     320 2459.17   363.7  2459.2   368.6 2461.84     373 2466.21
   390.8 2472.37   417.2 2470.96   426.9 2474.71   465.8 2474.17   488.5 2485.63
   497.6  2487.4   589.8 2492.03   634.4  2498.9   698.9 2503.87   865.3  2509.8
#Mann= 7 ,-1,0
       0      .1       0   311.1    .045       0   368.6      .1       0
  394.06     .06       0  579.56      .1       0  609.56     .05       0
  689.56      .1       0
#XS Ineff= 2 , 0
                             394            2500
Permanent Ineff=
       F       F
Bank Sta=311.1,368.6
XS Rating Curve= 0 ,0
Exp/Cntr=0.3,0.1

Type RM Length L Ch R = 1 ,36048   ,281.7,281.7,281.7
XS GIS Cut Line= 5
2219866.88167424541555.8398823162220067.86043641 541811.84655337
     2220190.803      541874.8292220561.55137136 542060.22091622
2220764.80451026542274.120551545
#Sta/Elev= 30
       0 2610.49    32.2 2594.94   103.4 2566.67   194.9 2520.34   215.9 2515.54
   240.7 2503.99   298.2 2488.13   330.3 2482.62   357.3 2480.43   375.3 2471.79
   397.7 2473.59   411.2 2465.21   424.7 2460.38   433.7 2456.97   487.3 2456.94
     492 2457.49  495.162460.889   502.2 2467.05   513.6 2468.75   540.4 2469.29
   603.8  2465.5   639.6 2465.88     653 2468.97   675.3 2484.81   772.9 2487.27
   827.4  2494.2   879.4 2496.12   957.1 2508.89  1092.9 2538.41  1173.2 2558.69
#Mann= 6 ,-1,0
       0      .1       0   424.7    .045       0  495.16      .1       0
  503.61     .07       0  613.61     .05       0  843.61      .1       0
#XS Ineff= 2 , 0
                             550            2520
Permanent Ineff=
       F       F
Bank Sta=424.7,495.16
XS Rating Curve= 0 ,0
Exp/Cntr=0.3,0.1

Type RM Length L Ch R = 1 ,35767   ,39.1,39.1,39.1
BEGIN DESCRIPTION:
structure
END DESCRIPTION:
XS GIS Cut Line= 5
2219750.21169157541925.4921323292219972.94071771542144.129495582
2220184.10157281542130.2429658222220242.56048241542159.417610564
2220337.11337106542477.479059868
#Sta/Elev= 30
       0 2537.16    50.9 2523.13   137.3 2507.98   153.7 2502.21   182.3 2502.09
   221.4 2495.03   233.1 2490.02   277.4 2478.29   288.6 2472.79   323.4 2474.66
   342.4 2466.46   383.5  2458.3  391.162454.744   395.5 2454.16   455.7 2454.66
   463.7 2455.61   471.7 2459.34   487.7 2460.94   499.7 2467.18   519.8 2467.74
   541.7 2464.96   581.9 2464.01   599.2 2468.99   624.3 2483.41   691.5 2486.28
   711.9 2489.41   753.6 2499.75   807.9 2507.45   824.6 2512.63   920.9 2526.53
#Mann= 6 ,-1,0
       0      .1       0  372.11     .08       0  391.16    .045       0
   455.7      .1       0  543.72     .06       0  573.72      .1       0
#XS Ineff= 2 , 0
                          515.55         2500.43
Permanent Ineff=
       F       F
Bank Sta=391.16,455.7
XS Rating Curve= 0 ,0
Exp/Cntr=0.3,0.1

Type RM Length L Ch R = 1 ,35728   ,564.3,564.3,564.3
BEGIN DESCRIPTION:
structure
END DESCRIPTION:
XS GIS Cut Line= 5
2219746.17874137541957.7557339632219968.90776751542176.393097216
2220180.06862261542162.5065674562220238.52753221542191.681212198
2220333.08042086542509.742661502
#Sta/Elev= 30
       0  2532.5      62 2516.69     117 2507.09   176.6 2499.02   216.2 2489.73
   233.3 2484.11   261.2 2478.67   273.3 2473.06   303.7 2472.45   316.5 2466.71
   359.4 2459.53  371.142454.088   376.5 2453.57   438.6 2454.04   451.7 2454.25
   475.7 2465.81   483.8 2466.88   511.8 2467.64   523.8 2464.64   555.6 2463.57
     573 2468.47     598 2482.91   640.7 2483.44   665.6 2486.25   686.6  2489.9
   726.7 2500.78   758.9 2504.38   819.4 2515.26   848.9 2518.39   920.9 2532.16
#Mann= 5 ,-1,0
       0      .1       0  371.14    .045       0   438.6     .08       0
  472.11     .06       0  583.72      .1       0
#XS Ineff= 2 , 0
                             510            2500
Permanent Ineff=
       F       F
Bank Sta=371.14,438.6
XS Rating Curve= 0 ,0
Exp/Cntr=0.3,0.1

Type RM Length L Ch R = 1 ,35163   ,501.6,501.6,501.6
XS GIS Cut Line= 4
2219565.12453287542163.479235481 2219645.5003861542538.018119199
2219759.40890904542651.1874086962219881.52720441542876.349787307
#Sta/Elev= 30
       0 2512.54    52.7 2509.94   198.1 2493.17   210.4 2488.25   230.8 2487.71
   255.4 2477.68   271.7 2473.64   344.2 2470.12   353.6 2468.06   364.4 2468.96
   382.2 2467.75   387.2 2465.05   392.8 2458.88   405.2 2451.73   409.8 2450.48
   465.8 2450.44   486.2 2451.65   500.3 2461.44   539.1 2463.89   564.1 2486.17
   572.2 2491.82   600.5 2507.37   614.2 2512.72   627.8 2521.64   656.1 2536.15
   700.6 2566.33   709.7 2568.85   718.8 2573.82   737.4 2588.99   799.8 2629.25
#Mann= 6 ,-1,0
       0      .1       0     380     .06       0   405.2    .045       0
   486.2     .06       0  513.07     .07       0  523.07      .1       0
Bank Sta=405.2,486.2
XS Rating Curve= 0 ,0
Exp/Cntr=0.3,0.1

Type RM Length L Ch R = 1 ,34662   ,431.2,431.2,431.2
XS GIS Cut Line= 4
2218998.24003801542499.5216604552219244.82885137542805.246200573
  2219384.070725 542993.479915882219583.26670629543236.170623705
#Sta/Elev= 30
       0 2517.96    89.5 2493.78   223.1 2473.48   326.8 2465.71   372.1 2458.83
   406.6 2459.88     432 2463.62     506 2448.01   512.1 2445.57   522.1 2445.54
   551.9 2445.59  558.552448.364   575.3 2460.42   606.8 2462.78   621.6 2477.96
   626.8 2487.47   631.7 2501.73   633.4  2504.5     642 2514.74     658 2529.77
   688.6 2551.93   717.7 2568.31   777.4 2609.34     791 2613.42   808.7 2627.29
   822.9 2645.07   833.5 2654.57   885.3 2682.33   904.5 2685.37   940.9 2702.22
#Mann= 6 ,-1,0
       0      .1       0     240     .05       0     300      .1       0
     506    .045       0  558.55     .06       0  676.91      .1       0
Bank Sta=506,558.55
XS Rating Curve= 0 ,0
Exp/Cntr=0.3,0.1

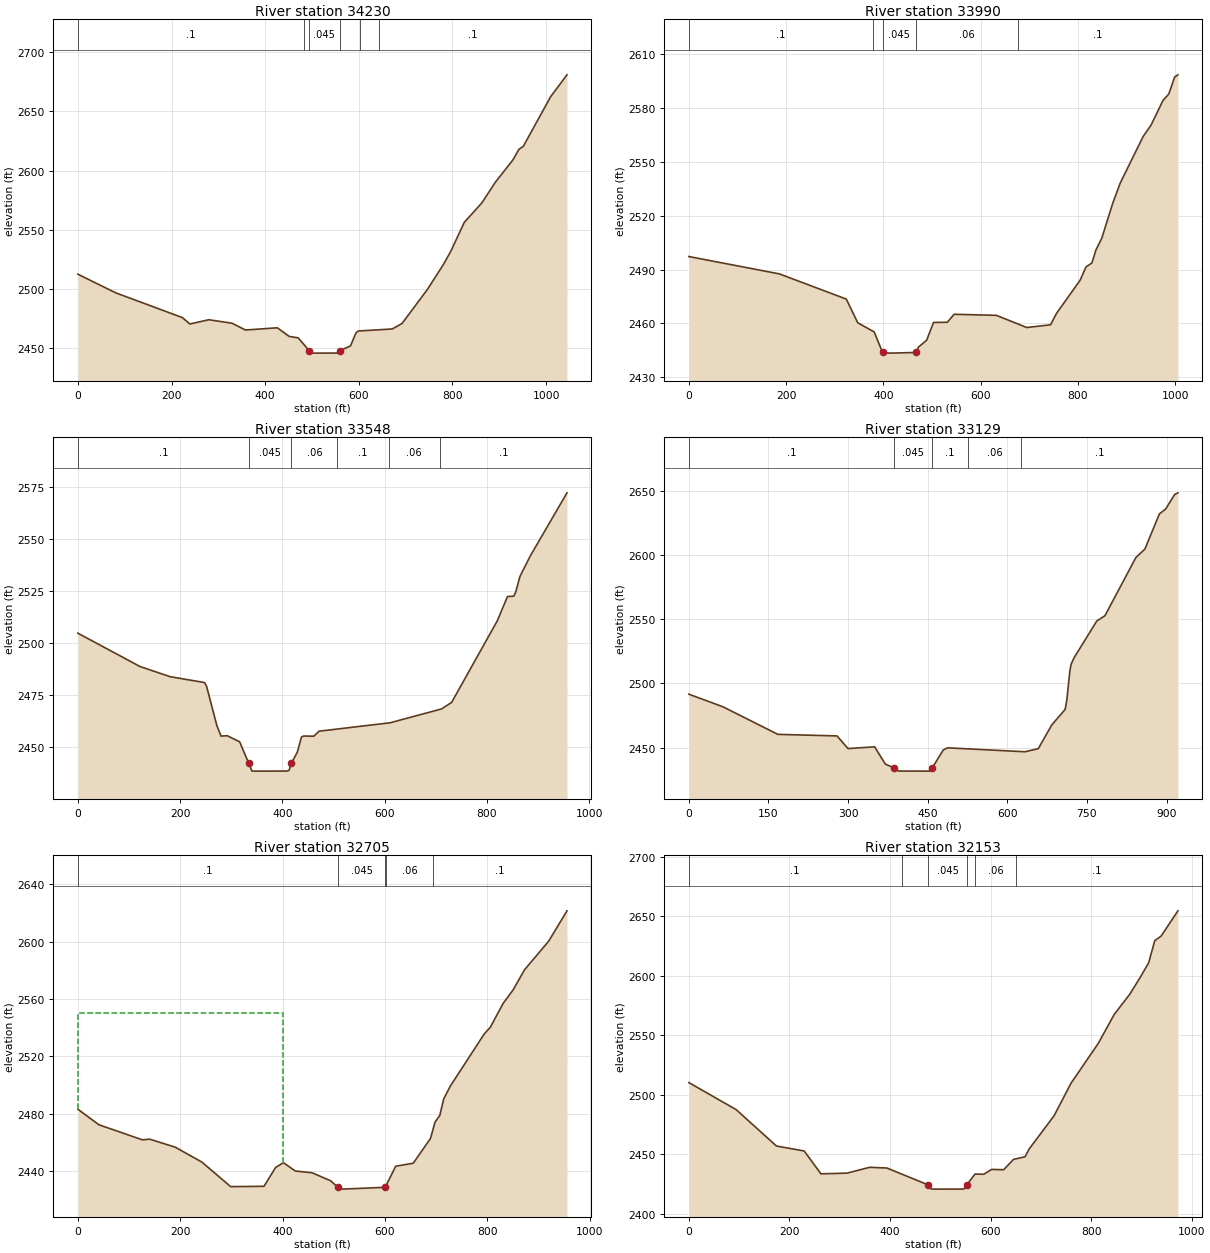
Type RM Length L Ch R = 1 ,34230   ,240.2,240.2,240.2
XS GIS Cut Line= 4
2218798.06595092 542687.735895192218835.85403229542988.529022924
2219039.90967171543248.5110227742219434.94479458543361.616331028
#Sta/Elev= 30
       0 2512.14    81.1 2496.29   223.2 2475.37   239.3 2469.95   279.6 2473.55
   329.4 2470.57     358 2464.84     426 2466.72   451.4 2459.39   470.6 2458.19
   494.2 2447.23   502.3 2445.25   553.1  2445.3  558.762447.175   582.3 2451.37
   593.8 2462.31   598.9 2464.01   671.4 2465.71   692.2 2470.33   746.3 2499.11
     780 2519.92   796.2 2531.36   825.3 2556.07   862.8 2572.57   891.9 2590.23
   929.3 2609.05   941.7 2617.81   951.4 2620.54  1009.6 2662.47  1044.6 2681.07
#Mann= 6 ,-1,0
       0      .1       0  483.16     .05       0   494.2    .045       0
  558.76     .05       0  603.16     .06       0  643.66      .1       0
Bank Sta=494.2,558.76
XS Rating Curve= 0 ,0
Exp/Cntr(USF)=0,0
Exp/Cntr=0.3,0.1

Type RM Length L Ch R = 1 ,33990   ,441.9,441.9,441.9
XS GIS Cut Line= 5
2218405.50308777543335.4359513762218721.56337727543242.538855798
2218793.66995335543323.3867810382218955.13619267543511.978998393
2219270.74227366543562.256153192
#Sta/Elev= 30
       0 2497.22   186.2 2487.56   323.8 2473.55   347.3 2460.38   381.2 2455.27
   398.3 2443.88   413.4 2443.48  467.152443.849   472.4 2446.89     489 2450.66
   503.2 2460.56   531.6 2460.65   545.4 2465.09   632.3  2464.5     695 2457.72
   743.8 2459.25   755.9 2465.55   804.5 2484.02   816.7 2491.45   828.8 2493.64
     837 2500.82   849.1 2507.43   871.6 2526.85   887.1 2538.15   934.2 2564.02
   950.4 2570.32   974.9 2584.03   986.8  2587.6   998.9 2597.05  1005.6  2598.3
#Mann= 5 ,-1,0
       0      .1       0  379.43     .05       0   398.3    .045       0
  467.15     .06       0  677.76      .1       0
Bank Sta=398.3,467.15
XS Rating Curve= 0 ,0
Exp/Cntr=0.3,0.1

Type RM Length L Ch R = 1 ,33548   ,419.5,419.5,419.5
XS GIS Cut Line= 5
 2218261.1671403543609.2305836972218494.13951387 543687.10236534
     2218614.912      543702.6472218967.55916741543744.536287325
2219199.42837206543774.884664311
#Sta/Elev= 30
       0 2504.82   121.3  2488.8   180.3  2483.9   247.7 2481.07   251.7 2479.26
   271.9 2460.29     280 2455.32   292.1  2455.5   316.3 2452.58  334.242442.182
   340.5 2438.48   364.7 2438.47     409 2438.51     413 2438.87   417.6 2442.31
   429.1 2447.58   437.2 2454.86   441.2 2455.34   461.3 2455.27   471.6 2457.68
   610.4 2461.71   711.1 2468.38   730.8 2471.51     820 2510.71   840.1 2522.47
   852.3 2522.58   856.3 2524.71   864.4  2532.1   884.5 2541.89   956.4 2572.32
#Mann= 6 ,-1,0
       0      .1       0  334.24    .045       0   417.6     .06       0
  507.41      .1       0  607.41     .06       0  707.41      .1       0
Bank Sta=334.24,417.6
XS Rating Curve= 0 ,0
Exp/Cntr=0.3,0.1

Type RM Length L Ch R = 1 ,33129   ,424.1,424.1,424.1
XS GIS Cut Line= 4
2218190.85192501543916.933317904 2218450.2441981544097.159938027
2218786.06754575544146.925055104     2218972.487      544336.818
#Sta/Elev= 30
       0 2491.63    64.4 2481.79   167.8 2460.33   279.2 2459.12     300 2449.28
   350.2 2450.62   370.3 2437.17   386.6 2434.28   394.6 2431.79   447.2 2431.71
   455.3 2431.74  458.792434.319   479.5 2448.25   487.6 2449.86   633.2 2446.79
   658.4 2449.18   683.9  2467.7     709 2479.71   712.2 2486.95   717.8  2509.2
   720.2 2514.89   726.3 2520.28   768.7 2548.62     784 2552.69   842.3    2598
   859.3 2604.61   886.7 2632.06   898.2 2635.62   915.3 2647.05   921.5 2648.39
#Mann= 5 ,-1,0
       0      .1       0   386.6    .045       0  458.79      .1       0
  525.86     .06       0  625.86      .1       0
Bank Sta=386.6,458.79
XS Rating Curve= 0 ,0
Exp/Cntr=0.3,0.1

Type RM Length L Ch R = 1 ,32705   ,552.2,552.2,552.2
XS GIS Cut Line= 4
2217970.68355316544076.3211148792218286.78383839 544385.25577424
2218399.33115557544515.2231138642218637.09549741544760.739971085
#Sta/Elev= 30
       0  2483.1    41.2 2472.22   126.1 2461.71   140.3 2462.18   190.1 2456.61
   242.6 2446.12   298.5 2429.04   363.7 2429.27   386.4 2442.46   401.8 2445.75
   424.7 2439.97   457.8  2438.7     494 2433.12   508.1 2428.56     516  2427.3
   600.6 2428.56   620.9 2443.28   655.4 2445.41     689 2462.68   697.9  2474.1
   707.1 2478.67   714.9 2490.36     728 2499.38   794.1 2535.67     806 2540.34
   830.9 2556.95   850.7  2566.5   872.8 2580.46   919.9 2600.37   955.7 2621.58
#Mann= 5 ,-1,0
       0      .1       0   508.1    .045       0   600.6      .1       0
     602     .06       0  693.92      .1       0
#XS Ineff= 2 , 0
             400    2550
Permanent Ineff=
       F       F
Bank Sta=508.1,600.6
XS Rating Curve= 0 ,0
Exp/Cntr=0.3,0.1

Type RM Length L Ch R = 1 ,32153   ,659.7,659.7,659.7
XS GIS Cut Line= 5
2217518.32874124544552.580997334 2217721.1004813544567.232244438
2217916.09196752544790.8787982062218031.30506085544912.756079161
2218324.04287214 544998.34172219
#Sta/Elev= 30
       0  2510.2    94.1 2487.48   174.3 2456.88   229.5 2452.69   262.8 2433.49
   314.6 2434.08   359.8 2438.99     394 2438.38   476.5 2424.14   481.8 2420.82
   487.1 2420.65     547  2420.7   552.6 2424.14   569.2 2433.31   586.6 2433.14
   602.3 2437.21   626.2 2436.95   645.7 2445.61   668.8 2447.88     677 2454.46
   726.3 2482.21   760.3 2509.75   814.5 2543.22   846.1 2567.46     877 2584.42
   898.1 2598.83   914.5 2610.78   926.7 2629.45   939.3 2633.23   972.7 2654.47
#Mann= 6 ,-1,0
       0      .1       0   423.3     .08       0   476.5    .045       0
   552.6     .07       0  570.01     .06       0  650.01      .1       0
Bank Sta=476.5,552.6
XS Rating Curve= 0 ,0
Exp/Cntr=0.3,0.1