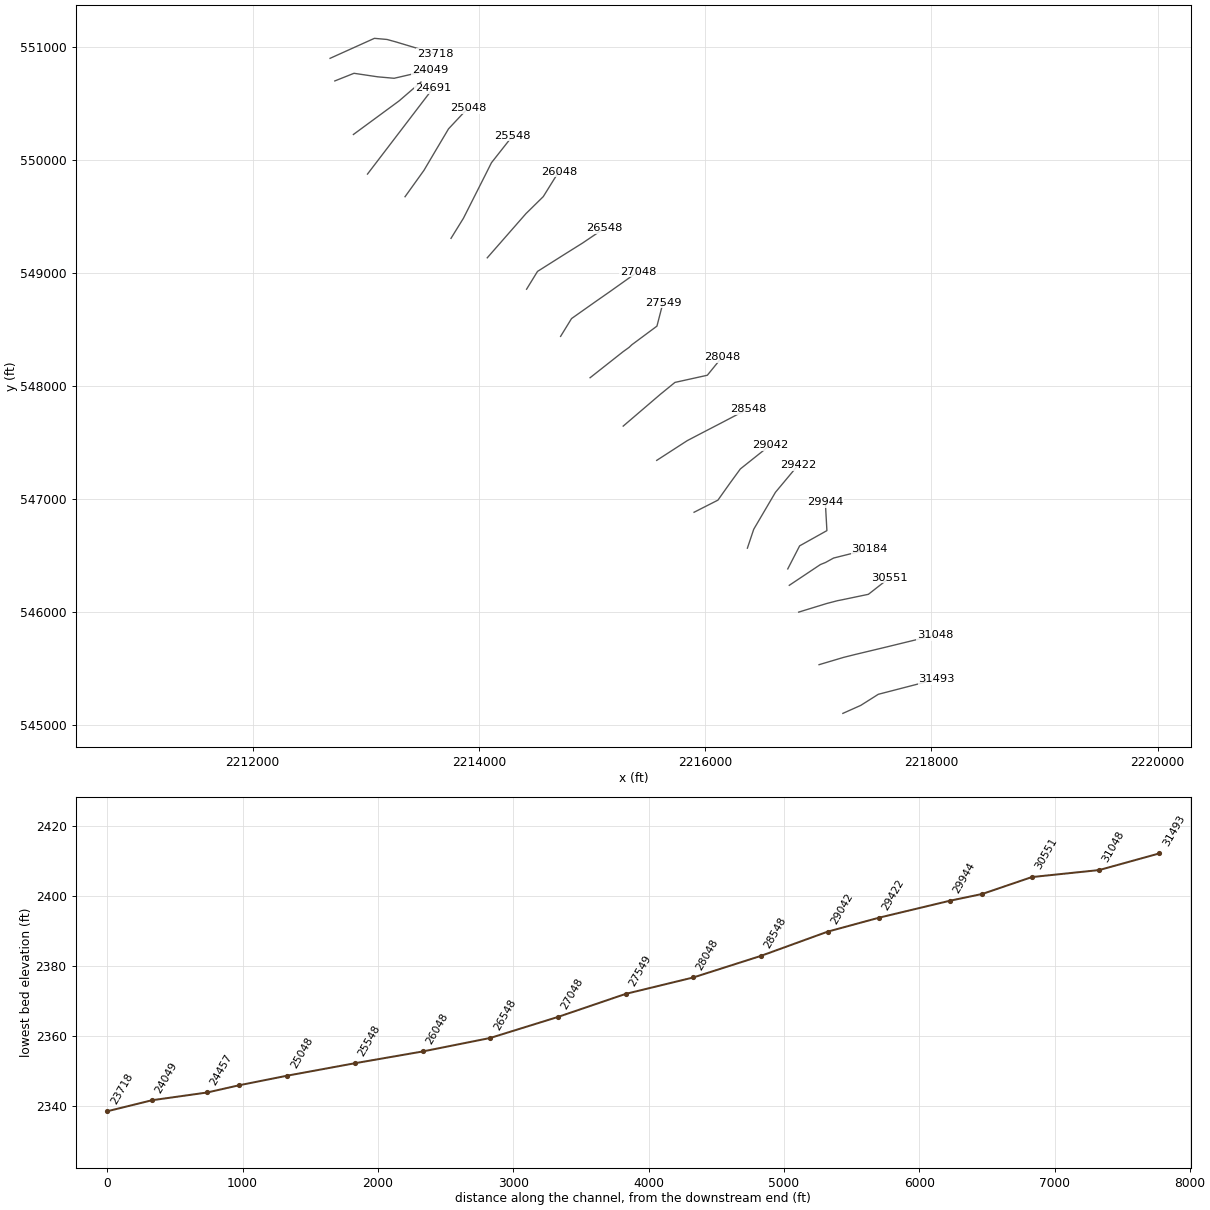
HEC-RAS study ELKRIV.prj: ELKRIV

--- ELKRIV.g01 (geometry) --- (continued)

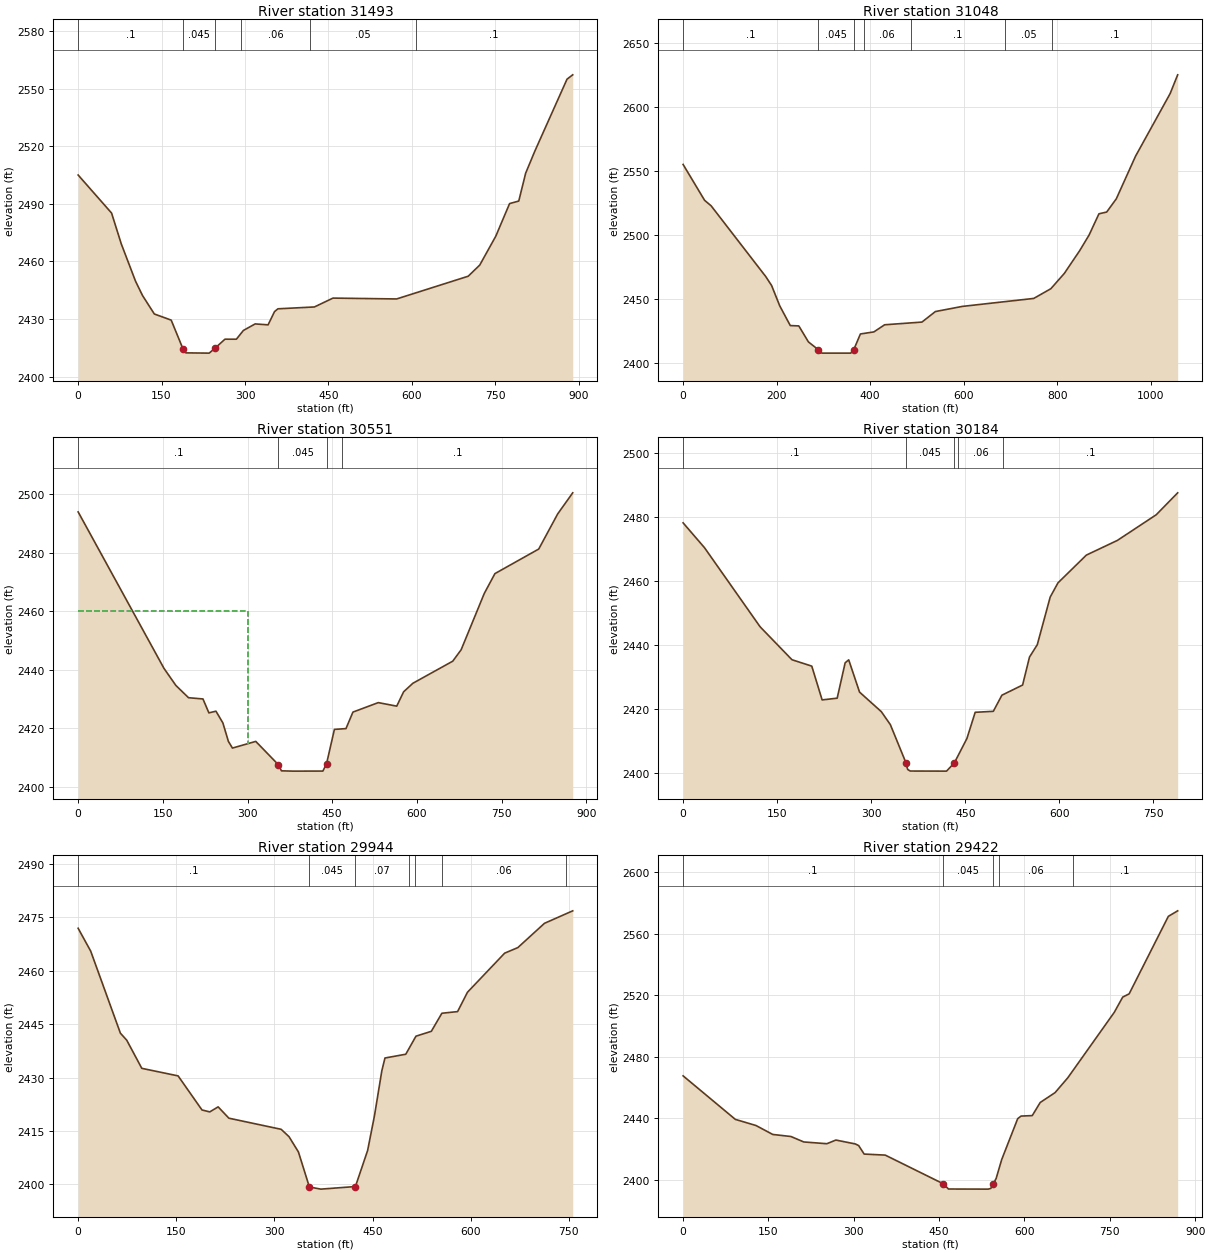
Type RM Length L Ch R = 1 ,31493   ,444.5,444.5,444.5
XS GIS Cut Line= 4
2217217.30478635545107.064089793 2217375.4375106545177.719955152
2217530.57021111545275.7506442822218046.08071495 545409.14815531
#Sta/Elev= 30
       0 2505.05    60.1 2485.22    77.6 2469.11   103.2 2449.69   115.8 2442.21
     137  2432.6   167.3 2429.41   188.3 2414.55   193.6 2412.33   235.6  2412.2
   245.8  2414.7     264 2419.47   284.5 2419.46   297.1 2424.02   318.3 2427.43
   341.5 2426.94   353.1 2433.85   359.2  2435.3   424.8 2436.27   458.2 2440.89
   572.6 2440.44   701.3 2452.29     722 2458.09   750.9 2473.16   775.7 2490.16
   792.2 2491.48   804.6 2506.01   821.1 2517.51     879 2555.03   889.2 2557.28
#Mann= 6 ,-1,0
       0      .1       0   188.3    .045       0   245.8      .1       0
   293.2     .06       0  416.71     .05       0  606.71      .1       0
Bank Sta=188.3,245.8
XS Rating Curve= 0 ,0
Exp/Cntr=0.3,0.1

Type RM Length L Ch R = 1 ,31048   ,497.5,497.5,497.5
XS GIS Cut Line= 5
2217006.74467081545537.4941297872217223.78975782545602.063205552
     2217321.072      545626.4582217605.02297753545694.502541302
2218031.73655683545798.625611602
#Sta/Elev= 30
       0 2555.13    45.9 2527.08    59.9 2522.77   176.8 2467.37   189.3 2460.38
   206.7 2444.49   229.3 2429.01   247.5 2428.75   268.1 2416.22   288.7 2410.28
   296.9 2407.45   358.7 2407.46   365.1  2410.2   379.3 2422.45   408.1 2424.05
   431.1 2429.64   510.9 2431.75   539.7 2439.99   597.3 2444.02   750.1 2450.26
   786.7 2457.87   815.5 2469.84   848.4 2487.67   868.5 2499.88   889.6  2516.5
   906.1 2517.87   926.7 2528.21   967.8 2561.54  1041.9 2610.61    1058 2625.27
#Mann= 7 ,-1,0
       0      .1       0   288.7    .045       0   365.1      .1       0
  386.74     .06       0  486.74      .1       0  688.73     .05       0
  788.73      .1       0
Bank Sta=288.7,365.1
XS Rating Curve= 0 ,0
Exp/Cntr=0.3,0.1

Type RM Length L Ch R = 1 ,30551   ,366.5,366.5,366.5
XS GIS Cut Line= 6
2216826.77668874546002.2748506422217075.32954706546078.568024952
2217170.53374619546103.3607851412217209.51228543546110.977143709
2217442.90366022546159.6602208132217631.57091335546307.131294813
#Sta/Elev= 30
       0 2493.85   152.1 2440.47   173.1 2434.67   195.5 2430.49   221.1 2430.06
   231.6 2425.31   244.1 2425.89   256.4 2421.87   266.1 2415.61   273.3 2413.31
   314.6 2415.59   354.7 2407.63   360.1 2405.55   380.4 2405.45   433.5 2405.47
     440 2407.98   453.9 2419.68   474.4 2419.95   486.7 2425.58   531.6 2428.81
   564.3 2427.61   576.5  2432.5   592.9 2435.41   663.5 2442.94   678.4 2446.84
   719.4 2466.06   738.2  2472.8   815.8 2481.18   849.4 2493.16     876 2500.35
#Mann= 4 ,-1,0
       0      .1       0   354.7    .045       0     440     .07       0
  468.09      .1       0
#XS Ineff= 2 , 0
             300    2460
Permanent Ineff=
       F       F
Bank Sta=354.7,440
XS Rating Curve= 0 ,0
Exp/Cntr=0.3,0.1

Type RM Length L Ch R = 1 ,30184   ,240.1,240.1,240.1
XS GIS Cut Line= 5
2216743.76176637546239.2726667852217019.20025641546423.046546374
 2217063.7080682546440.8566564192217135.20047148546480.217642496
2217453.38505901546559.970197211
#Sta/Elev= 30
       0 2478.19    34.2 2470.41   122.8 2445.72   173.6 2435.43   205.2 2433.43
   221.7 2422.88   245.7 2423.42   258.4 2434.46   264.1  2435.4   281.4 2425.31
   316.1 2419.21   330.5 2415.16  355.442403.202   358.1 2401.16   362.3 2400.66
   420.1 2400.63432.63022403.232   452.6 2410.83   465.8 2419.01   494.7 2419.31
   508.4 2424.35   541.4 2427.53   552.4 2436.26   564.8 2440.12   585.4    2455
   597.8 2459.44   643.1 2468.12   692.6 2472.71   754.5 2480.72   788.7 2487.57
#Mann= 5 ,-1,0
       0      .1       0  355.44    .045       0432.6302      .1       0
  439.06     .06       0  510.67      .1       0
Bank Sta=355.44,432.6302
XS Rating Curve= 0 ,0
Exp/Cntr=0.3,0.1

Type RM Length L Ch R = 1 ,29944   ,521.9,521.9,521.9
XS GIS Cut Line= 4
2216730.16023395546384.1468605412216835.18169758546587.951926796
2217076.28426938546722.8259891632217062.29761387546972.897947203
#Sta/Elev= 30
       0 2471.94    19.2 2465.52    64.6 2442.48    74.3 2440.51    97.3 2432.61
   152.8 2430.49   189.3 2420.92   201.2 2420.38     214 2421.79   230.4 2418.61
   310.3 2415.49   322.3 2413.43   336.7 2409.14   353.5 2399.28   371.1 2398.69
  423.842399.416   442.5 2409.54     453 2419.33   464.2 2431.91     469 2435.51
   500.8 2436.57   516.4 2441.64   539.9 2443.01     556 2448.08     580 2448.54
   595.1 2453.97     652 2464.96   672.1 2466.51   712.8 2473.33     756 2476.84
#Mann= 7 ,-1,0
       0      .1       0   353.5    .045       0  423.84     .07       0
  505.54     .06       0  515.54     .07       0  555.54     .06       0
  745.54      .1       0
Bank Sta=353.5,423.84
XS Rating Curve= 0 ,0
Exp/Cntr(USF)=0,0
Exp/Cntr=0.3,0.1

Type RM Length L Ch R = 1 ,29422   ,380.3,380.3,380.3
XS GIS Cut Line= 4
 2216373.3985989546567.7001607212216429.26381253546734.439118265
2216621.30351007547061.3448955332216822.67807892547302.699935198
#Sta/Elev= 30
       0 2467.57    91.8 2439.25   128.1 2435.26   157.6 2429.44   189.5 2428.11
   212.1 2424.56   252.7 2423.42   268.5  2425.8   302.7 2423.27   308.6  2422.2
   318.2 2416.68   355.3    2416   457.4 2397.33   466.4 2393.94   536.2 2393.87
   540.9 2394.34  545.012397.309   550.2 2400.78     560 2413.12   588.1  2439.7
     594  2441.4   613.7 2441.71   627.7 2450.25   653.8 2456.66   676.2 2466.32
   757.9 2508.92   772.7 2518.82     784 2520.92   852.9 2571.35   869.3 2574.94
#Mann= 5 ,-1,0
       0      .1       0   457.4    .045       0  545.01      .1       0
  554.99     .06       0  684.99      .1       0
Bank Sta=457.4,545.01
XS Rating Curve= 0 ,0
Exp/Cntr=0.3,0.1

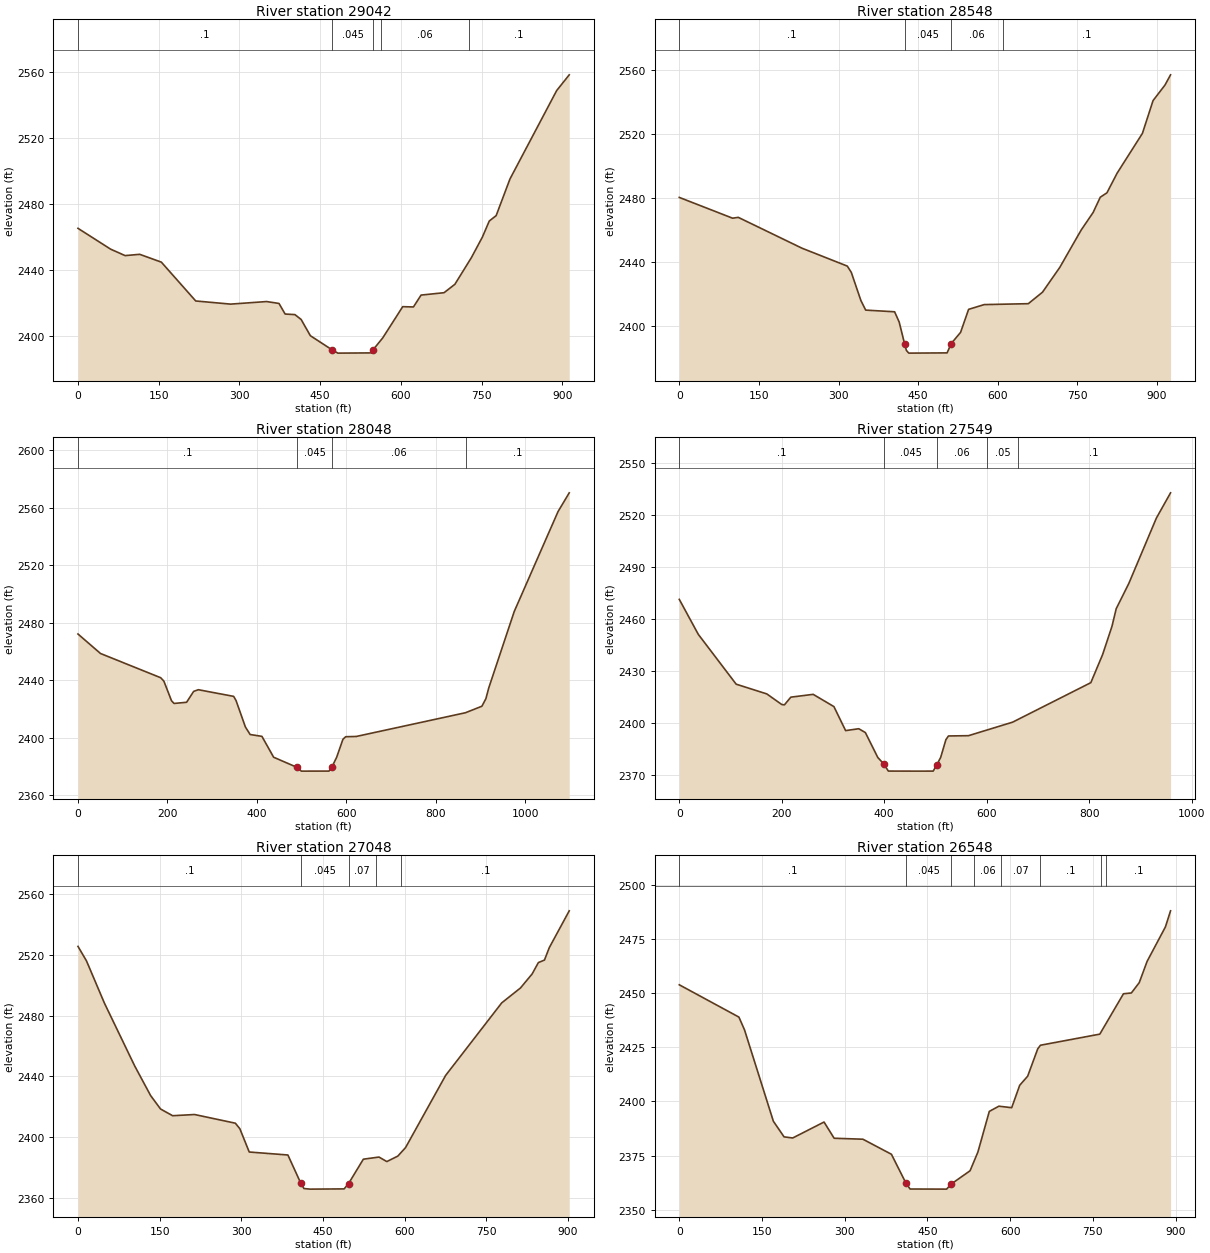
Type RM Length L Ch R = 1 ,29042   ,493.7,493.7,493.7
XS GIS Cut Line= 5
 2215902.0587375 546885.075434422216112.87244193546992.148428975
2216220.90852612547144.3907288962216311.38990893547268.308704731
 2216574.4293209547477.725954711
#Sta/Elev= 30
       0 2465.29    60.7 2452.69    87.6  2448.8   114.7 2449.58   154.9 2444.86
   218.8 2421.39   283.6 2419.49   350.5 2421.04   373.5  2419.9   384.9  2413.5
   403.1 2413.15   414.6 2410.23   431.8 2400.41   471.8 2391.94   482.9 2389.88
   543.4 2390.01  548.492391.969   566.3  2399.1   603.4 2417.95   623.3 2417.77
   637.5 2424.95   680.2 2426.39   700.3 2431.46     731 2447.58   751.4 2459.98
   764.2 2469.69     777 2472.96   802.7 2495.12   889.5 2548.54   912.8 2558.03
#Mann= 5 ,-1,0
       0      .1       0   471.8    .045       0  548.49      .1       0
  563.13     .06       0  726.56      .1       0
Bank Sta=471.8,548.49
XS Rating Curve= 0 ,0
Exp/Cntr=0.3,0.1

Type RM Length L Ch R = 1 ,28548   ,500.1,500.1,500.1
XS GIS Cut Line= 5
2215571.90333384547343.6439864132215841.51983795547517.988552705
     2215974.023      547587.2692216144.88255523547675.791580527
     2216377.367      547797.836
#Sta/Elev= 30
       0 2480.18   100.4 2467.21   111.2 2467.72   231.2 2448.47   316.6 2437.29
   324.1 2433.36   342.1 2415.87   351.2 2409.82   405.7 2408.77   414.3 2402.36
  424.732388.435   427.9 2384.64   432.4 2382.96   504.6 2383.11   512.2 2388.88
     530 2395.93   545.1 2410.29   574.5 2413.26   657.6 2413.83   684.3    2421
   716.9 2436.48   757.1 2459.76   779.7 2470.77   793.2 2480.31   805.7 2483.04
   824.9  2495.3   872.6 2520.18   892.6 2540.61   915.2 2550.38   925.6 2556.72
#Mann= 4 ,-1,0
       0      .1       0  424.73    .045       0   512.2     .06       0
   610.6      .1       0
Bank Sta=424.73,512.2
XS Rating Curve= 0 ,0
Exp/Cntr=0.3,0.1

Type RM Length L Ch R = 1 ,28048   ,499.2,499.2,499.2
XS GIS Cut Line= 5
2215275.67463748547646.6559833942215603.52611516547927.354195384
2215733.01182305548032.9495804182216019.22436518548096.222782264
2216149.86477143548256.680781215
#Sta/Elev= 30
       0 2472.22    50.4 2458.66     185  2441.8   192.2 2439.38   209.2 2425.76
   214.9  2423.9   242.9  2424.7   258.7 2432.29   269.2 2433.46   348.2 2428.82
   353.5 2425.93   374.5 2407.49   385.1 2402.27   411.4    2401   437.6 2386.47
   490.2 2379.38   499.5  2376.8   561.5 2376.83  567.772379.591   578.4 2386.33
   592.6 2398.97   598.7 2400.74   622.4 2400.92   866.6 2417.43   903.4 2421.97
   912.3 2427.22   918.8  2434.8   975.7 2487.89  1073.6 2557.38  1098.7 2570.47
#Mann= 4 ,-1,0
       0      .1       0   490.2    .045       0  567.77     .06       0
  868.68      .1       0
Bank Sta=490.2,567.77
XS Rating Curve= 0 ,0
Exp/Cntr=0.3,0.1

Type RM Length L Ch R = 1 ,27549   ,500.6,500.6,500.6
XS GIS Cut Line= 6
2214983.05365409 548074.376681262215276.77758034548306.084051857
2215327.07589977548342.2626434782215352.16324302548365.998326604
2215573.88776378548530.5365260712215627.01715365548735.887123821
#Sta/Elev= 30
       0 2471.21    37.1 2451.03     111 2422.29   170.8 2416.67   200.1 2410.54
   205.2 2410.36   217.7  2414.8   261.3 2416.42   301.8 2409.35   324.6  2395.5
   350.3 2396.58   363.2 2394.36   387.4    2380     400 2375.98   407.9 2372.15
   464.4 2372.12   495.5 2372.13   502.8 2375.85   510.1 2380.01   520.4 2390.31
   525.4 2392.41   564.4 2392.57   650.5 2400.36   803.2 2423.16   826.3 2439.45
   844.5  2455.7   852.7  2465.8   877.5  2480.5   931.1 2518.09   958.8 2532.69
#Mann= 5 ,-1,0
       0      .1       0     400    .045       0   502.8     .06       0
  600.61     .05       0  660.61      .1       0
Bank Sta=400,502.8
XS Rating Curve= 0 ,0
Exp/Cntr=0.3,0.1

Type RM Length L Ch R = 1 ,27048   ,500,500,500
XS GIS Cut Line= 5
2214722.28433486548439.9136108422214818.98364153548597.355419099
     2215033.545      548748.8652215153.76965089548832.613197953
     2215405.301      549011.207
#Sta/Elev= 30
       0 2525.64    15.6 2516.11    48.4 2488.36   104.1 2446.85   133.5 2427.22
   151.7 2418.39   173.9 2413.96   214.2 2414.75   289.1 2409.02   297.4 2405.35
   314.6 2390.02   385.6 2388.05   409.4 2369.37   415.1 2365.91   426.6 2365.54
   488.9 2365.69     497 2369.18   524.2 2385.28     553 2386.69   567.3 2383.72
   587.5 2387.31   601.8 2392.97   675.4 2440.56   778.4 2488.39   812.8 2498.21
   834.2 2507.44   845.7 2514.96   856.9 2516.63   865.7 2524.78   902.4  2549.1
#Mann= 5 ,-1,0
       0      .1       0   409.4    .045       0     497     .07       0
  547.43     .06       0  593.95      .1       0
Bank Sta=409.4,497
XS Rating Curve= 0 ,0
Exp/Cntr=0.3,0.1

Type RM Length L Ch R = 1 ,26548   ,500,500,500
XS GIS Cut Line= 5
2214421.61091405548857.0647586452214518.22158675549014.211891204
     2214754.683      549163.6722214915.86755734 549264.61852469
2215111.89491289549396.956480892
#Sta/Elev= 30
       0 2453.84   108.1 2438.94   118.3 2433.03   170.6 2390.88     190 2383.67
   205.7 2383.15   262.5 2390.51   280.8 2383.03     333 2382.58   384.7 2375.64
   411.3 2362.18   418.6  2359.6   484.8 2359.55  492.762361.843   527.3 2368.02
   541.5 2376.64   562.2 2395.42   579.6 2397.82   602.8 2397.13   617.3 2407.46
   631.8 2411.67     650 2424.27     655 2425.95   762.6 2431.07   805.5  2449.7
   819.8 2450.06   834.1 2454.82   848.4 2464.66   881.6 2480.56   890.9 2487.97
#Mann= 8 ,-1,0
       0      .1       0   411.3    .045       0  492.76      .1       0
  534.21     .06       0  584.21     .07       0  654.21      .1       0
  764.39     .07       0  774.39      .1       0
Bank Sta=411.3,492.76
XS Rating Curve= 0 ,0
Exp/Cntr=0.3,0.1

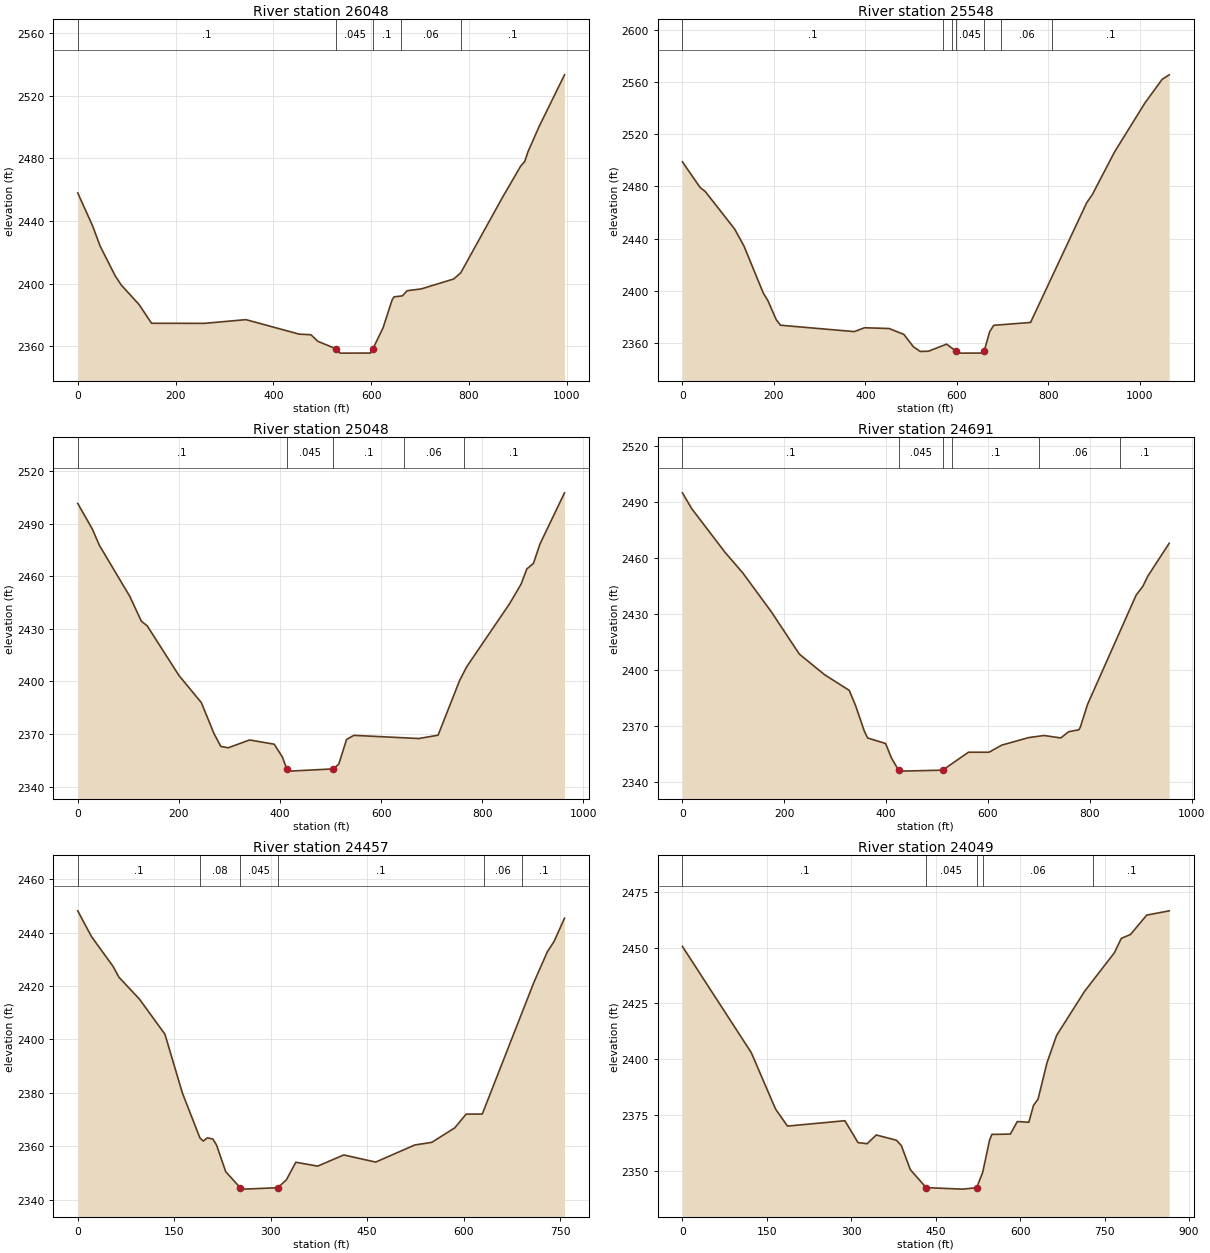
Type RM Length L Ch R = 1 ,26048   ,500,500,500
XS GIS Cut Line= 5
2214073.98999414549134.4451123322214417.30787476 549526.50829459
     2214445.223      549553.5822214569.15047752549675.502269542
2214707.18224432 549897.38176019
#Sta/Elev= 30
       0 2457.89    30.2 2437.03      46 2423.85    76.2 2405.22    88.7 2399.24
   125.4 2386.69   150.9 2374.74   258.8 2374.69   343.9 2377.06   452.6 2367.81
   476.8 2367.41     491 2363.19   527.9  2358.5   536.3 2355.69   598.6 2355.74
   603.62358.599   624.1 2371.76   642.7 2389.68   646.7 2391.62   663.7 2392.24
   673.5 2395.53     702 2396.65   768.8 2403.02     783 2406.94   868.3 2455.06
   905.4 2474.97   913.8 2477.97   920.2 2483.98   943.1 2500.22   995.2  2533.3
#Mann= 5 ,-1,0
       0      .1       0   527.9    .045       0   603.6      .1       0
  660.02     .06       0  783.87      .1       0
Bank Sta=527.9,603.6
XS Rating Curve= 0 ,0
Exp/Cntr=0.3,0.1

Type RM Length L Ch R = 1 ,25548   ,500,500,500
XS GIS Cut Line= 5
2213753.67564776549306.690674131  2213863.631255549484.529384836
     2214051.687      549856.7932214110.95562244549974.850855638
 2214300.0641744550214.856255839
#Sta/Elev= 30
       0 2498.84    38.5 2479.26      50 2476.09   114.1 2447.39   134.4 2434.48
   176.9  2398.2   186.7 2392.62   205.1  2377.9   214.3 2373.71   375.6 2368.82
     398 2371.78   451.8 2371.19   483.9 2366.68   504.7 2357.23   519.6 2353.63
   537.5 2353.79   577.3 2359.22   598.8 2353.65   608.7 2352.34     654 2352.38
   659.6 2354.07   671.3 2368.63   680.3 2373.65   760.8 2375.83   883.4 2467.46
   895.9 2473.85   944.5 2506.49  1010.7  2543.9  1048.5 2562.07  1063.8 2565.48
#Mann= 7 ,-1,0
       0      .1       0  569.09     .08       0  589.09      .1       0
   598.8    .045       0   659.6      .1       0  696.15     .06       0
  808.25      .1       0
Bank Sta=598.8,659.6
XS Rating Curve= 0 ,0
Exp/Cntr=0.3,0.1

Type RM Length L Ch R = 1 ,25048   ,357.5,357.5,357.5
XS GIS Cut Line= 5
2213347.30098943549674.4963353462213514.73843166549908.100917659
     2213605.026         550061.2213731.85961667550274.775937859
2213902.33880462550456.481112789
#Sta/Elev= 30
       0 2501.73      29 2487.01    42.7 2477.84   102.9 2448.66   125.8 2434.45
   137.3 2431.83   200.3 2403.38   244.4 2387.95   269.3 2370.35     283 2362.89
   297.7 2362.14   339.8 2366.59   388.5 2364.18   404.8 2356.81   413.22350.147
   418.7 2348.79  505.172350.066   516.3 2352.82   531.6 2366.92   546.2 2369.23
   674.7 2367.42   712.6 2369.32   755.2 2400.56   769.2 2408.43     854 2444.44
   876.8 2455.67   888.1  2464.3   901.1 2467.45   914.3 2478.69   962.7  2507.8
#Mann= 5 ,-1,0
       0      .1       0   413.2    .045       0  505.17      .1       0
  644.98     .06       0  763.55      .1       0
Bank Sta=413.2,505.17
XS Rating Curve= 0 ,0
Exp/Cntr=0.3,0.1

Type RM Length L Ch R = 1 ,24691   ,234.5,234.5,234.5
XS GIS Cut Line= 2
 2213015.3726534549874.7416802262213595.63784938550634.412540656
#Sta/Elev= 30
       0 2494.97    18.2 2486.52    83.6 2463.16   118.8 2452.03   174.2 2431.45
   229.6 2408.67   279.1 2397.65   327.6 2389.25   340.3 2380.94   357.2 2367.43
   363.8 2363.77     399 2360.83   410.4 2353.12   424.7 2346.41   429.6 2346.04
  511.092346.563   561.6 2356.15     602 2356.15   627.3 2359.98   680.1    2364
     710 2365.11     743 2363.81   758.5 2367.13   778.5 2368.17   781.4 2369.61
   795.6 2381.78   890.9 2440.21   904.1 2444.91   914.1 2450.48   955.9 2467.98
#Mann= 6 ,-1,0
       0      .1       0   424.7    .045       0  511.09     .08       0
     530      .1       0     700     .06       0     860      .1       0
Bank Sta=424.7,511.09
XS Rating Curve= 0 ,0
Exp/Cntr(USF)=0,0
Exp/Cntr=0.3,0.1

Type RM Length L Ch R = 1 ,24457   ,407.6,407.6,407.6
XS GIS Cut Line= 3
2212890.92968688550224.7917003982213294.64759158550521.591606716
2213488.46050733550688.649206052
#Sta/Elev= 30
       0 2448.15    21.4  2438.5    54.7 2427.44    64.1 2423.29    95.9 2415.12
   135.6 2401.96   162.7 2379.99     190 2363.14   195.2 2361.98   201.5 2363.19
   210.1 2362.74   215.8 2360.52   230.1 2350.53  252.62 2344.52   258.7 2343.99
  311.05 2344.52   324.5 2347.49   339.1 2354.06   373.1  2352.6   413.6 2356.78
   463.3 2354.11   524.2 2360.52   550.6  2361.5   586.2  2366.9     604 2372.07
   629.1 2372.09     709 2421.17   730.2 2432.79   740.7 2436.69     757  2445.4
#Mann= 6 ,-1,0
       0      .1       0     190     .08       0  252.62    .045       0
  311.05      .1       0  631.08     .06       0  691.08      .1       0
Bank Sta=252.62,311.05
XS Rating Curve= 0 ,0
Exp/Cntr(USF)=0,0
Exp/Cntr=0.3,0.1

Type RM Length L Ch R = 1 ,24049   ,330.5,330.5,330.5
XS GIS Cut Line= 5
2212726.55237013550698.1404533312212896.15818385550765.628237056
2213105.26096507550734.5348343212213250.70782355550721.595497735
 2213567.1049683550794.723708436
#Sta/Elev= 30
       0 2450.56   122.3 2402.97   165.3 2377.74   186.6 2370.04   288.6 2372.44
     312 2362.62   328.1 2362.14   344.3 2366.05   380.1  2363.7   388.8 2361.35
   404.9 2350.48     433 2342.46     497 2341.78  522.622342.382   533.4 2349.31
   545.6 2363.74   549.7  2366.3   582.5 2366.45   594.8 2372.07   615.4 2371.76
   623.6 2379.28   631.8 2382.18   647.5 2398.34   664.6 2410.64   714.2 2430.38
   767.3 2447.72   779.6 2454.18     796 2455.92   824.7 2464.59   864.7 2466.52
#Mann= 5 ,-1,0
       0      .1       0     433    .045       0  522.62      .1       0
  533.94     .06       0  729.96      .1       0
Bank Sta=433,522.62
XS Rating Curve= 0 ,0
Exp/Cntr=0.3,0.1

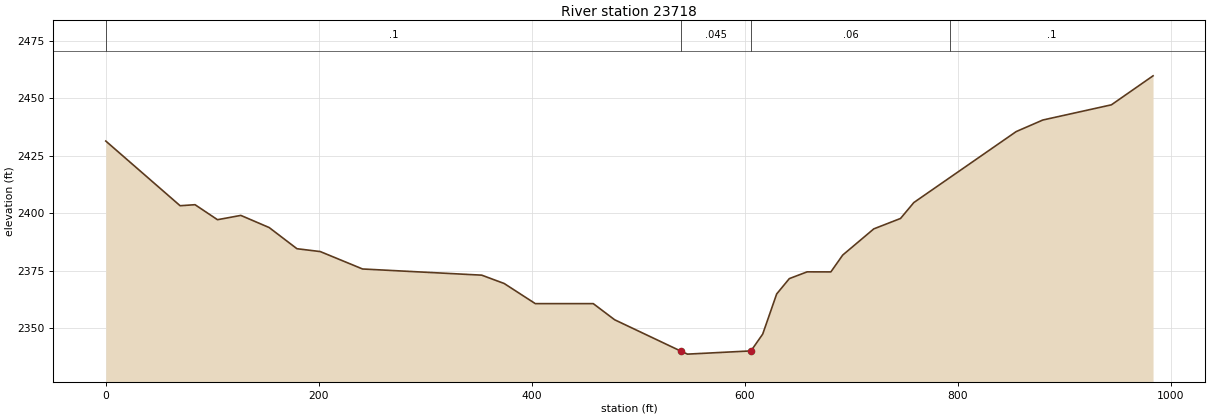
Type RM Length L Ch R = 1 ,23718   ,277.3,277.3,277.3
XS GIS Cut Line= 5
2212684.56419528550897.9476027292213076.63888591551074.747116503
2213187.95770296551064.7619579462213265.60862788551043.341013142
2213611.29811397550939.597247516
#Sta/Elev= 30
       0 2431.31    69.8 2403.18    83.8 2403.62   104.9  2397.1   126.8 2398.97
   153.4 2393.69   179.5 2384.48   201.4 2383.24   241.1 2375.67     353 2372.98
   374.1 2369.35   403.3  2360.6   457.7  2360.6   477.8 2353.58  539.832339.967
   546.2 2338.64   605.8 2340.04   616.8 2347.36   629.9  2364.8   641.8 2371.48
   658.5 2374.42   680.8  2374.4   691.9 2381.71   721.1 2393.11   746.2 2397.64
   758.7 2404.56   854.8 2435.42   879.8 2440.45   944.2 2447.06   983.3 2459.67
#Mann= 4 ,-1,0
       0      .1       0  539.83    .045       0   605.8     .06       0
  792.41      .1       0
Bank Sta=539.83,605.8
XS Rating Curve= 0 ,0
Exp/Cntr(USF)=0,0
Exp/Cntr=0.3,0.1