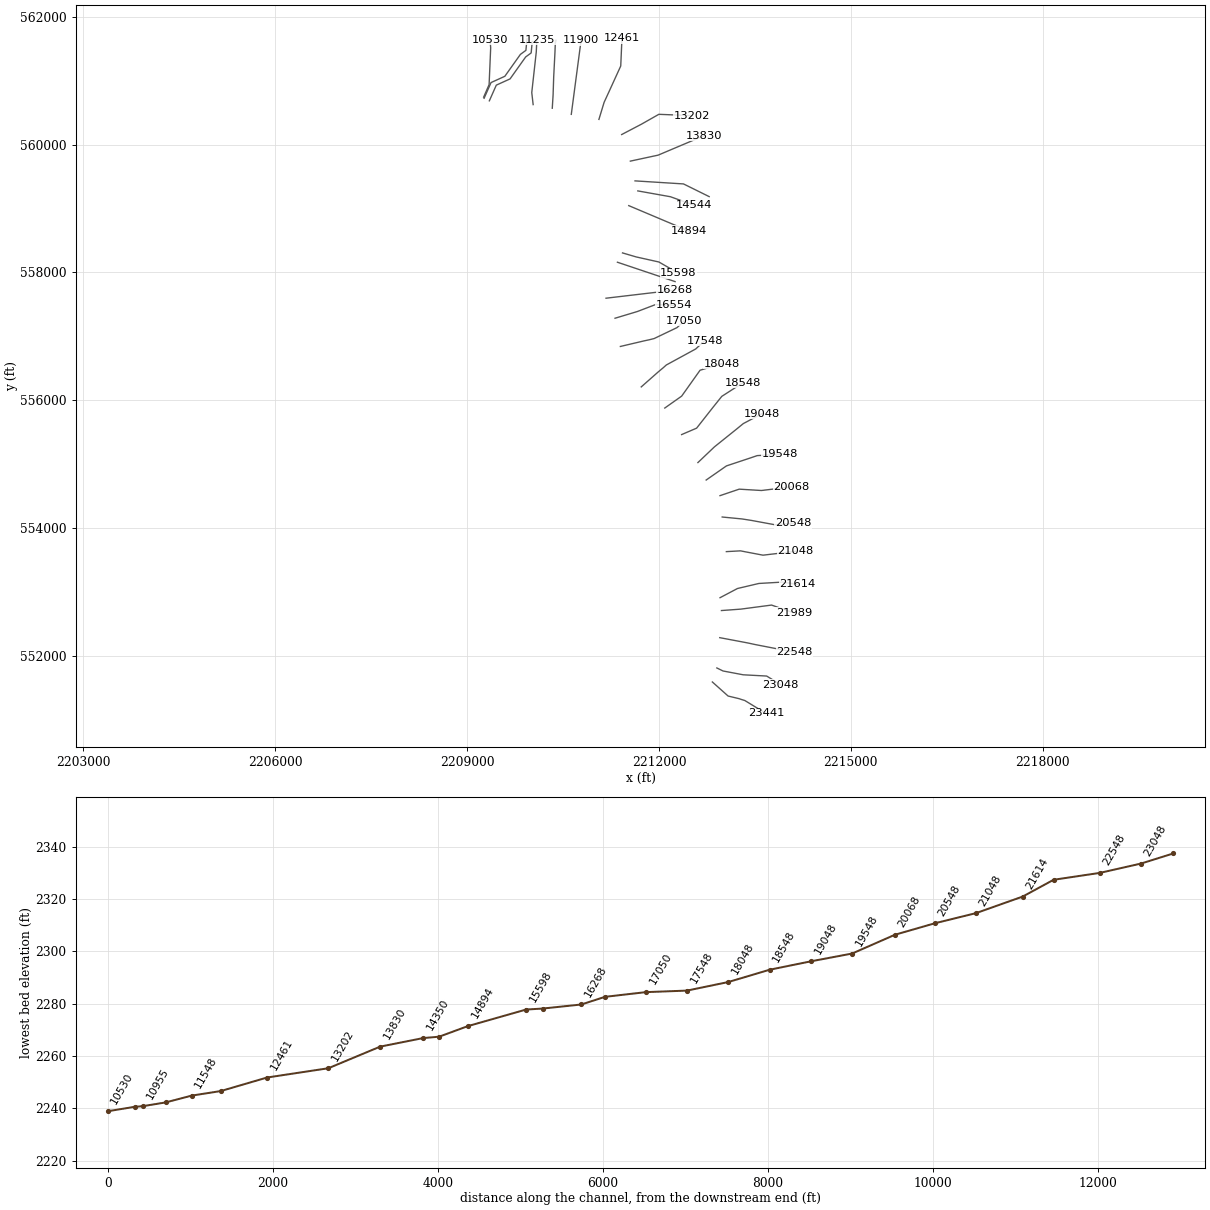
HEC-RAS study ELKRIV.prj: ELKRIV

--- ELKRIV.g01 (geometry) --- (continued)

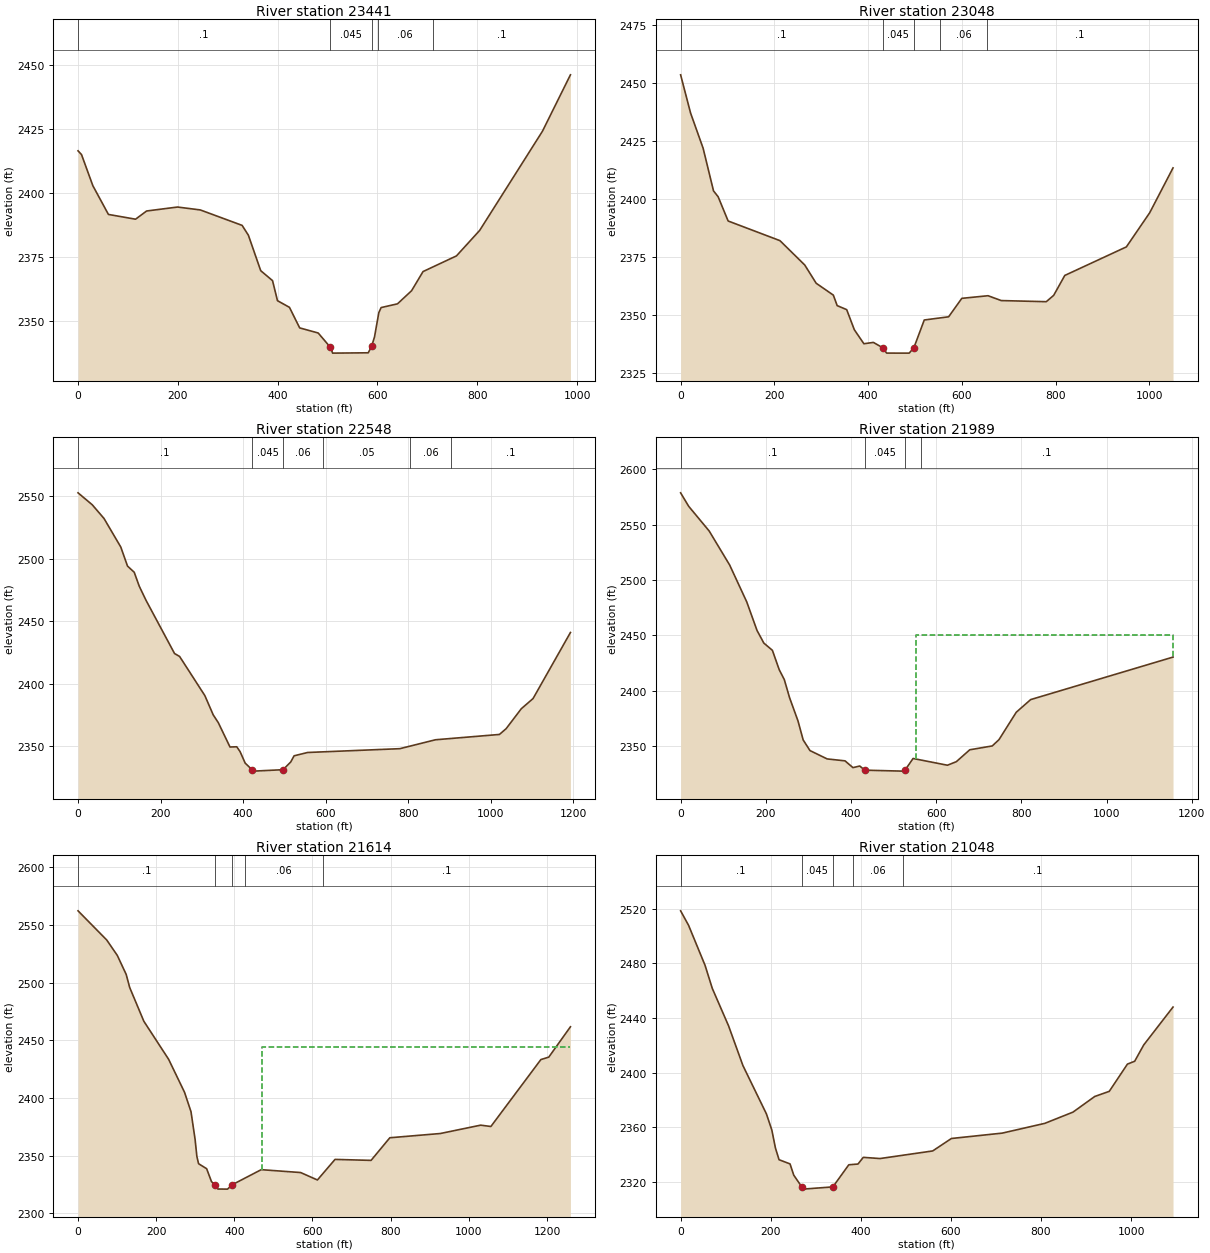
Type RM Length L Ch R = 1 ,23441   ,392.7,392.7,392.7
XS GIS Cut Line= 6
2212834.99072478551597.9898695812213081.03322289551378.195375674
2213250.79359171551337.3880890562213294.41434591551322.746042273
2213342.61862946551308.0040769782213672.08093897551107.047693481
#Sta/Elev= 30
       0 2416.49       7 2415.02    29.7 2402.87    60.9 2391.65   115.3 2389.79
   137.4 2392.99   199.4 2394.54     245 2393.41   328.8 2387.38   341.4 2383.53
   366.1 2369.69   389.8  2365.8   399.7 2357.97   423.7 2355.37   444.2 2347.34
   481.3 2345.35   505.8 2339.75   510.2 2337.49   581.6 2337.62   588.4 2340.12
   594.2 2343.87   602.8  2353.3   607.4 2355.28   640.2 2356.74   668.4 2361.85
   691.4 2369.34   758.4 2375.46   804.9 2385.41   930.7 2424.14   986.8 2446.17
#Mann= 5 ,-1,0
       0      .1       0   505.8    .045       0   588.4      .1       0
  600.53     .06       0  710.94      .1       0
Bank Sta=505.8,588.4
XS Rating Curve= 0 ,0
Exp/Cntr=0.3,0.1

Type RM Length L Ch R = 1 ,23048   ,500,500,500
XS GIS Cut Line= 6
2212905.12133233551817.2027023972213001.70448302551769.839739333
2213317.30488446551710.227053589     2213362.013      551707.766
 2213683.9692541551690.6180202412213901.10572216551557.674829555
#Sta/Elev= 30
       0  2453.4    21.2 2436.99      48 2421.81    70.2 2403.44      80 2400.94
   101.4 2390.48   211.9 2382.03   264.8 2371.55   289.2 2363.69   325.8 2358.58
     334 2354.06   354.3 2352.33   370.6 2343.68     391 2337.65   411.3 2338.22
   430.7 2335.98   439.6 2333.62   487.7 2333.61   497.82336.015   519.8 2347.87
   571.8 2349.25   599.9 2357.19   655.9 2358.32     684 2356.23   780.1 2355.75
   795.9 2358.48   819.6 2367.05     951 2379.34  1000.8 2394.05  1050.5 2413.34
#Mann= 5 ,-1,0
       0      .1       0   430.7    .045       0   497.8      .1       0
  553.53     .06       0  653.53      .1       0
Bank Sta=430.7,497.8
XS Rating Curve= 0 ,0
Exp/Cntr=0.3,0.1

Type RM Length L Ch R = 1 ,22548   ,559.1,559.1,559.1
XS GIS Cut Line= 5
     2212950.407      552290.7712213315.06893287552222.008043725
     2213397.457       552206.092213503.43079806552183.141900671
2214121.03441786552063.110900384
#Sta/Elev= 30
       0 2552.93    34.4 2543.37    62.9  2532.4   103.6 2509.49   119.8 2494.28
   136.1  2489.3   148.3 2478.11   164.6 2466.89   233.8  2424.2     246 2421.88
   307.1 2390.56   327.4  2375.1   339.7 2368.87   368.1 2349.35   384.4 2349.54
   392.6 2345.59   404.8 2336.46   421.9 2331.05   425.2 2330.04  496.572331.183
   515.1 2337.34   523.3 2342.31     556 2344.97   779.4 2348.02   865.7 2355.15
  1020.6 2359.41  1036.9 2364.06  1073.5 2379.98  1102.1 2388.18  1192.6 2441.07
#Mann= 6 ,-1,0
       0      .1       0   421.9    .045       0  496.57     .06       0
  593.43     .05       0  803.43     .06       0  903.43      .1       0
Bank Sta=421.9,496.57
XS Rating Curve= 0 ,0
Exp/Cntr=0.3,0.1

Type RM Length L Ch R = 1 ,21989   ,375,375,375
XS GIS Cut Line= 4
2212977.28939366552714.5996516342213281.55841907552737.006358392
2213760.40017855552800.2233172382214107.65442452552678.471362342
#Sta/Elev= 30
       0 2578.79    18.9 2566.65    67.1 2544.29   115.2 2513.54   155.3 2480.25
   179.4 2454.47   195.4 2443.06   215.5 2436.53   231.5 2419.04   243.5 2410.04
   255.8 2393.76   275.6 2372.74   287.7 2355.62   303.7 2345.98     344 2338.44
     386 2336.69   404.6 2330.57   420.7 2332.02   432.3 2328.27   521.4 2327.41
  526.962328.336   545.8 2338.83   626.5 2332.74   647.3 2335.93   678.9 2346.69
   731.7 2350.17   747.5 2355.85   788.1 2380.62   821.9 2392.03  1156.1 2430.42
#Mann= 4 ,-1,0
       0      .1       0   432.3    .045       0  526.96     .06       0
  565.09      .1       0
#XS Ineff= 2 , 0
                             553            2450
Permanent Ineff=
       F       F
Bank Sta=432.3,526.96
XS Rating Curve= 0 ,0
Exp/Cntr=0.3,0.1

Type RM Length L Ch R = 1 ,21614   ,565.9,565.9,565.9
XS GIS Cut Line= 5
 2212955.1841696552915.5225867612213227.29131969 553059.03914281
2213562.61194526553137.995000436 2213936.3459135553159.787910036
2214166.84385342553121.926786913
#Sta/Elev= 30
       0 2562.13    73.5 2536.83   100.6 2523.43   123.2 2507.06   132.2 2495.71
   168.4 2466.45   231.8 2433.51   272.5 2404.94   289.1 2388.07   299.6 2363.99
   304.1 2349.33   308.5 2343.01   329.1 2338.69   341.4 2327.61   349.6 2324.56
   357.9 2321.08   382.5 2320.99   394.8 2324.84   468.8 2337.85   569.6 2335.36
   612.6 2328.92   657.7 2346.75   749.9 2345.89   797.9  2365.5     927 2369.17
  1030.4 2376.42  1056.5 2375.26  1184.4 2433.23  1204.7 2435.39  1260.1 2461.66
#Mann= 5 ,-1,0
       0      .1       0   349.6    .045       0   394.8      .1       0
  427.64     .06       0  627.64      .1       0
#XS Ineff= 2 , 0
                             470            2444
Permanent Ineff=
       F       F
Bank Sta=349.6,394.8
XS Rating Curve= 0 ,0
Exp/Cntr=0.3,0.1

Type RM Length L Ch R = 1 ,21048   ,500,500,500
XS GIS Cut Line= 5
2213053.98000088553635.6843843332213274.98459877553647.876009193
     2213355.694      553631.8312213626.83765386553580.255161278
2214136.72624867553640.279335998
#Sta/Elev= 30
       0 2518.53    17.7  2507.9    54.3 2478.57    70.3 2461.72   106.4 2434.31
   138.4 2405.11   190.5 2369.75   202.5 2357.92   210.5 2344.74   218.5 2336.21
   242.9 2333.13   251.1 2324.92   268.9 2316.33   271.5 2314.66  337.962316.295
   373.3 2332.49   393.7 2333.04   405.5 2337.94   442.6 2337.06   559.5 2342.63
   601.1 2351.75   713.9 2355.69   808.4 2362.84     871 2371.08   919.3 2382.54
   951.5 2386.29   991.8 2406.24  1007.9 2408.34    1028  2420.3    1093 2448.04
#Mann= 5 ,-1,0
       0      .1       0   268.9    .045       0  337.96     .05       0
  383.63     .06       0  493.63      .1       0
Bank Sta=268.9,337.96
XS Rating Curve= 0 ,0
Exp/Cntr=0.3,0.1

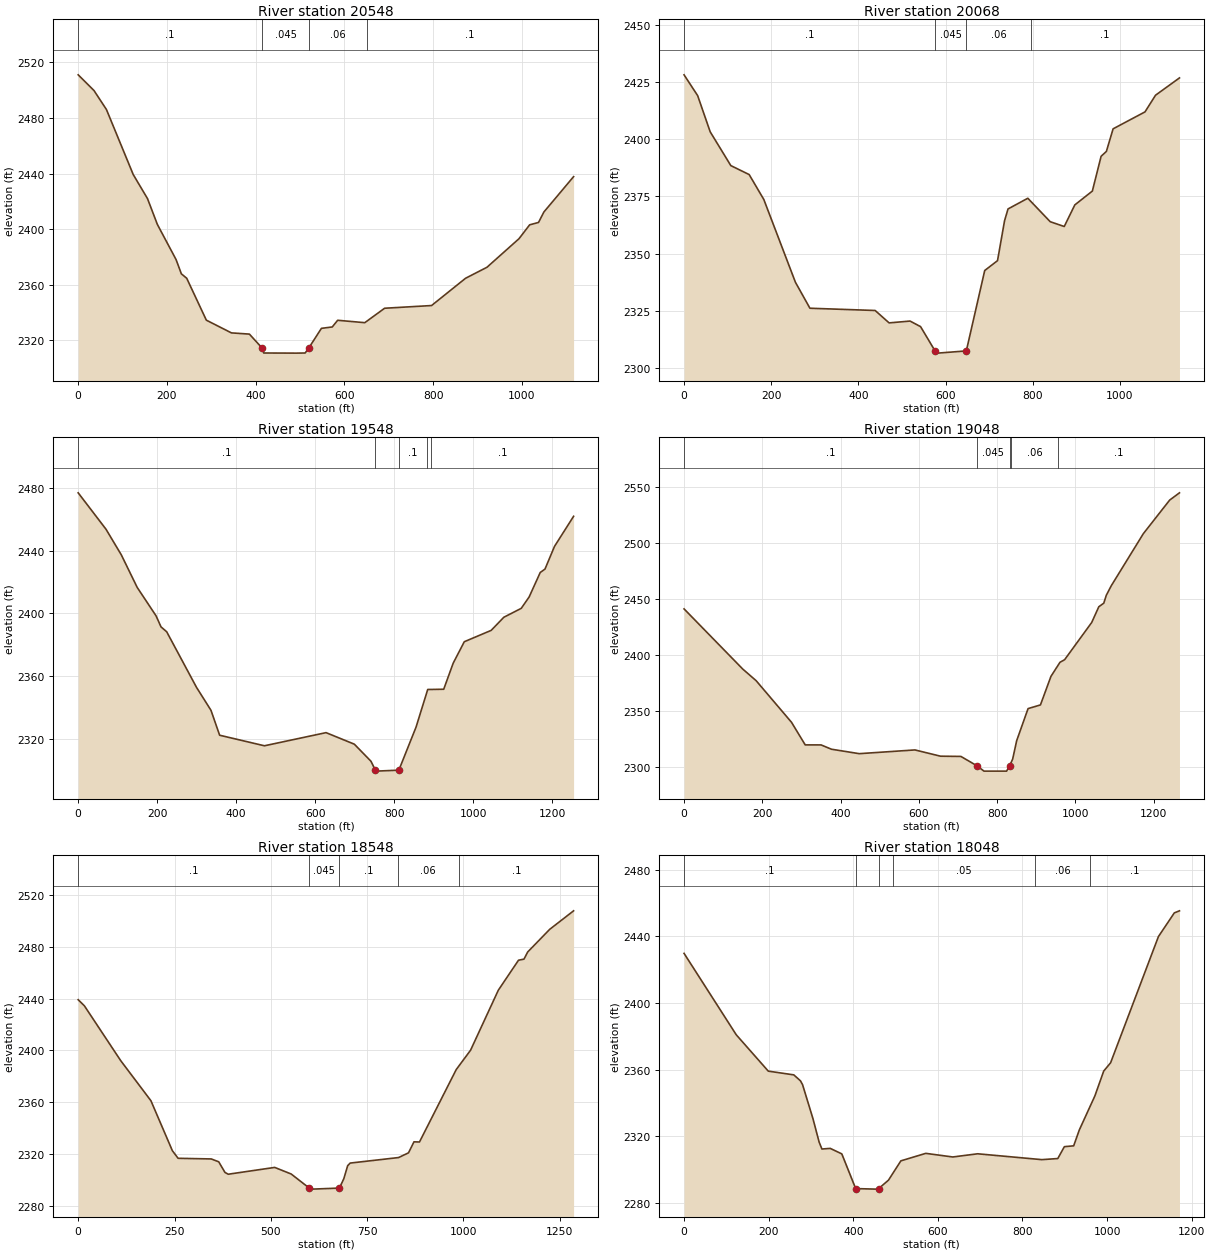
Type RM Length L Ch R = 1 ,20548   ,480.8,480.8,480.8
XS GIS Cut Line= 5
2212988.75960633554176.7643583612213300.06689002554146.453047325
      2213445.77      554123.6272213810.78787322554056.173246647
2214094.97774999554075.707301544
#Sta/Elev= 30
       0 2511.03    35.6 2499.74    63.7 2486.05     124  2439.3   156.2 2421.95
   178.5 2403.33   220.5 2378.13   232.5 2367.84   244.6 2364.62   288.8 2334.48
   345.3 2325.34   385.8 2324.45   414.1 2314.56   418.2 2310.86   491.2 2310.77
   511.5 2310.86   520.1 2314.71   548.1  2328.6   572.5  2329.6   584.7 2334.41
   645.8 2332.68   690.5 2343.07   796.3 2345.01   872.9 2364.64   921.1 2372.55
   993.2 2393.08  1017.3 2403.09  1037.3 2404.81  1049.4 2412.33  1116.3 2437.76
#Mann= 4 ,-1,0
       0      .1       0   414.1    .045       0   520.1     .06       0
  650.26      .1       0
Bank Sta=414.1,520.1
XS Rating Curve= 0 ,0
Exp/Cntr=0.3,0.1

Type RM Length L Ch R = 1 ,20068   ,519.2,519.2,519.2
XS GIS Cut Line= 4
 2212954.6303582 554510.777413412213254.53139271554612.241938269
2213602.53003657554591.3023771252214070.61551125554648.285648704
#Sta/Elev= 30
       0 2428.28    31.2 2419.17    59.9 2403.35   107.3 2388.53   149.4  2384.6
     183  2373.7   255.5 2337.46   288.8 2326.07   438.5 2325.08   470.5 2319.65
   518.6 2320.45   542.7 2318.01  576.632307.164   581.9 2306.41   647.7 2307.38
   689.9 2342.58   719.3 2346.91   735.4 2364.36   743.4 2369.55   788.8 2374.23
   840.2 2363.96   872.4 2361.86   896.6  2371.3   936.9 2377.38     957 2392.61
   969.1 2394.74   984.5 2404.63  1057.7 2412.05  1081.9 2419.35  1136.8 2426.93
#Mann= 4 ,-1,0
       0      .1       0  576.63    .045       0   647.7     .06       0
  795.23      .1       0
Bank Sta=576.63,647.7
XS Rating Curve= 0 ,0
Exp/Cntr=0.3,0.1

Type RM Length L Ch R = 1 ,19548   ,500,500,500
XS GIS Cut Line= 5
2212738.33695362554755.0328838232213055.20939761554975.759082347
     2213432.993      555101.4612213536.58636491555136.744505337
2213896.47667975555157.191963765
#Sta/Elev= 30
       0 2477.12    70.5 2453.82   109.2 2437.46   149.4 2416.66   197.2 2398.47
   209.7 2391.42   224.1 2388.29   299.6 2352.75   336.2  2338.1   358.1 2322.17
   471.5 2315.42   627.5 2323.82   699.1 2316.45   741.3 2305.52   752.42299.781
   753.9 2299.22   811.8 2299.82   855.3 2327.31   884.9  2351.4   925.4 2351.56
   949.4 2368.23   977.5 2381.94  1045.6  2389.2  1077.6 2397.58  1121.7 2403.28
  1141.7 2410.57  1169.8 2426.21  1181.8 2428.37  1205.8 2442.85  1254.2 2462.11
#Mann= 5 ,-1,0
       0      .1       0   752.4    .045       0   811.8      .1       0
  884.32     .06       0  893.76      .1       0
Bank Sta=752.4,811.8
XS Rating Curve= 0 ,0
Exp/Cntr=0.3,0.1

Type RM Length L Ch R = 1 ,19048   ,500,500,500
XS GIS Cut Line= 5
2212609.27426806555027.8247886752212867.12726907555273.097003006
     2213203.132      555542.7452213319.17422001555637.471849671
 2213610.3133209555791.743759325
#Sta/Elev= 30
       0 2441.29   150.1 2387.46   184.1 2377.13   274.5 2339.95   309.6  2319.7
   350.2 2319.67   376.6 2315.83   447.7 2311.85     590 2315.19   655.4 2309.59
   707.5 2309.38   749.3 2300.86   766.4 2296.24   824.2 2296.24   831.8 2300.89
   839.7 2306.97     850 2323.47   879.1 2352.15   910.7 2355.42   937.6 2380.98
   960.7 2393.57   972.5 2395.87  1041.7 2429.13  1059.9 2443.21  1072.6 2446.42
    1079 2453.44  1091.5 2461.87  1173.7 2508.57  1240.9 2538.55    1266 2545.07
#Mann= 5 ,-1,0
       0      .1       0   749.3    .045       0   831.8     .05       0
   836.7     .06       0  956.49      .1       0
Bank Sta=749.3,831.8
XS Rating Curve= 0 ,0
Exp/Cntr=0.3,0.1

Type RM Length L Ch R = 1 ,18548   ,500,500,500
XS GIS Cut Line= 5
2212354.73304969555465.4506379872212589.09129814555566.165727283
     2212832.521      555875.7432212982.25462831556062.739452538
2213316.30620867556277.994612879
#Sta/Elev= 30
       0 2439.17    16.1 2434.47   110.4 2392.16   188.8 2361.24   244.5 2322.66
   259.4 2316.81   345.4 2316.32   364.8 2314.11     381 2305.91   389.5 2304.53
   510.1 2309.78   552.8 2304.71  598.922294.047     607 2293.03   678.1 2293.83
   689.5 2301.08   699.5 2311.11   705.9 2313.13   831.8  2317.4   857.4 2321.04
   871.6 2329.52   885.9 2329.41   981.3 2385.29  1018.5 2400.21  1090.6 2446.55
  1142.9 2469.64  1157.2  2470.5  1166.7 2475.97  1223.8 2493.45  1285.9 2507.76
#Mann= 5 ,-1,0
       0      .1       0  598.92    .045       0   678.1      .1       0
  828.91     .06       0  988.46      .1       0
Bank Sta=598.92,678.1
XS Rating Curve= 0 ,0
Exp/Cntr=0.3,0.1

Type RM Length L Ch R = 1 ,18048   ,500,500,500
XS GIS Cut Line= 5
2212091.34675271555880.5068182072212355.19118239556066.756802664
     2212419.706      556157.3332212642.97175418556471.486851568
2212979.79923697556572.243224383
#Sta/Elev= 30
       0 2429.77   123.4 2380.92   199.1 2359.12   259.4 2356.88   275.2 2353.29
   280.1 2351.03   304.6 2330.69   319.3 2316.54   325.9 2312.39   345.5 2312.78
   372.9 2309.47   405.7 2288.65   453.6 2288.33   460.2 2288.68   483.2  2293.7
   512.5 2305.29   571.4 2309.79   635.2 2307.62   694.1 2309.53   845.9 2306.02
   883.5 2306.68     899  2313.8     921  2314.3   934.4 2323.86   971.1 2344.22
     992 2359.15  1008.3 2364.13  1121.4 2439.87    1159 2454.08  1171.1  2455.3
#Mann= 6 ,-1,0
       0      .1       0   405.7    .045       0   460.2      .1       0
  494.16     .05       0  829.57     .06       0  959.57      .1       0
Bank Sta=405.7,460.2
XS Rating Curve= 0 ,0
Exp/Cntr=0.3,0.1

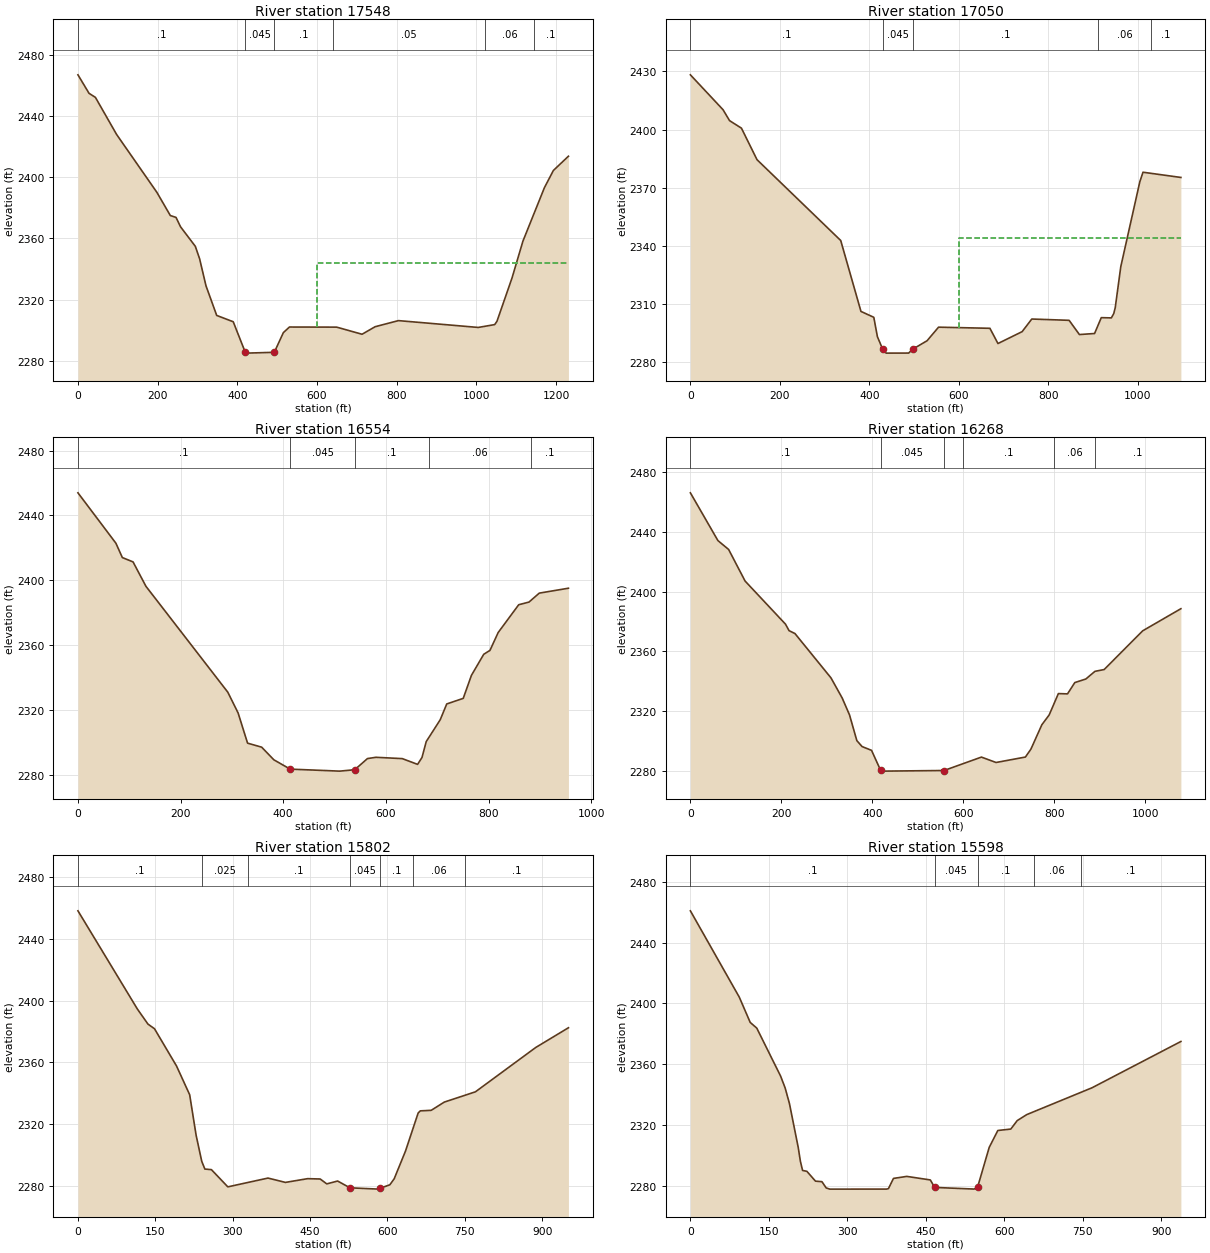
Type RM Length L Ch R = 1 ,17548   ,498.3,498.3,498.3
XS GIS Cut Line= 6
      2211723.27      556210.7862211984.95816319556441.692987021
      2212066.24       556509.752212115.41813284556553.518685297
2212574.97606734556804.0494101472212712.63474339556930.126990634
#Sta/Elev= 30
       0 2466.98    27.9 2454.87    43.9 2452.23    97.2 2427.93   197.9 2390.25
   231.9 2374.99   246.1 2373.79   257.5 2367.63   294.6 2354.87   305.3 2346.76
   321.3 2329.11   348.2  2309.7   389.7 2305.57  419.842285.662     423 2285.06
   492.8  2285.6   515.5 2298.46   530.8 2302.12   649.3 2302.05     713  2297.4
   745.8 2302.32   804.2 2306.31  1004.6 2301.85  1045.9 2303.72  1051.6 2305.91
  1089.3 2334.18  1116.7 2358.28  1170.6  2393.2  1193.1 2404.46  1230.9 2413.77
#Mann= 6 ,-1,0
       0      .1       0  419.84    .045       0   492.8      .1       0
  640.84     .05       0 1020.84     .06       0 1144.25      .1       0
#XS Ineff= 2 , 0
                             600            2344
Permanent Ineff=
       F       F
Bank Sta=419.84,492.8
XS Rating Curve= 0 ,0
Exp/Cntr=0.3,0.1

Type RM Length L Ch R = 1 ,17050   ,496.4,496.4,496.4
XS GIS Cut Line= 6
2211397.10652731556843.0508192942211769.60342698556930.733151215
2211843.58593816 556946.581938162211924.70179003556966.643797681
2212282.42158823557137.6871333742212398.52459535557244.516303854
#Sta/Elev= 30
       0 2428.28      73 2410.24    87.5 2404.62   114.1 2400.72   148.9 2384.43
     336 2342.66   381.2 2306.02   409.9 2302.98     418 2292.94  429.362286.713
   437.4 2284.47   487.8  2284.5   497.3 2286.56     529 2290.88   554.6 2297.88
   669.4  2297.3   687.4 2289.43   741.4 2295.57     763 2302.09   846.4 2301.42
   869.4 2294.07   903.3 2294.61   918.3  2302.8   940.8 2302.68   946.2 2304.92
   949.5    2308   961.9 2329.17  1004.4    2373  1011.5 2377.95  1096.2 2375.25
#Mann= 5 ,-1,0
       0      .1       0  429.36    .045       0   497.3      .1       0
   911.9     .06       0 1028.41      .1       0
#XS Ineff= 2 , 0
                             600            2344
Permanent Ineff=
       F       F
Bank Sta=429.36,497.3
XS Rating Curve= 0 ,0
Exp/Cntr=0.3,0.1

Type RM Length L Ch R = 1 ,16554   ,285.7,285.7,285.7
XS GIS Cut Line= 4
 2211313.3484265557284.2709099222211663.43729674557389.698329452
2211951.16964437557499.4919868972212232.98472064 557485.50845739
#Sta/Elev= 30
       0 2453.95      74 2422.93    86.5 2414.12   107.4 2411.43   132.5 2396.42
     292 2331.25   312.1 2318.45   330.5 2299.89     358 2297.41   381.6 2289.67
   413.5  2283.9     510 2282.67   539.3 2283.52   564.1 2290.39   580.5 2291.18
   631.9 2290.37   661.8 2286.83   670.4  2291.1   678.6 2300.84   705.9  2314.3
   718.6 2324.02   750.7 2327.44   766.7 2341.63   790.7 2354.59   802.8 2356.98
   818.8 2367.97   858.8 2385.07   878.8 2386.71   898.9 2392.22   955.7 2395.24
#Mann= 5 ,-1,0
       0      .1       0   413.5    .045       0   539.3      .1       0
  683.59     .06       0  883.59      .1       0
Bank Sta=413.5,539.3
XS Rating Curve= 0 ,0
Exp/Cntr=0.3,0.1

Type RM Length L Ch R = 1 ,16268   ,466,466,466
XS GIS Cut Line= 2
2211172.65825071557597.4788169972212243.76267103557723.796462689
#Sta/Elev= 30
       0  2466.3    60.5  2434.3    84.1 2428.32   120.3 2407.16     209 2378.31
     217  2373.9   229.9 2371.98   309.1 2342.27   333.8 2328.76   349.9 2317.42
     366 2300.19   377.6  2296.2   398.3 2293.68   418.4 2280.19   422.4 2279.75
   557.7 2280.16   639.9 2289.16   672.1 2285.54   736.6 2289.18   748.7 2294.46
   772.8 2310.82   788.9 2317.42   809.1 2331.72   829.2 2331.53   845.3 2339.12
   869.5  2341.5   889.6 2346.64   909.8 2347.84   994.4 2373.78  1078.5 2388.62
#Mann= 6 ,-1,0
       0      .1       0   418.4    .045       0   557.7     .08       0
     600      .1       0     800     .06       0     890      .1       0
Bank Sta=418.4,557.7
XS Rating Curve= 0 ,0
Exp/Cntr(USF)=0,0
Exp/Cntr=0.3,0.1

Type RM Length L Ch R = 1 ,15802   ,204.1,204.1,204.1
XS GIS Cut Line= 2
2211350.88725765 558159.851897132212252.41456457557857.035623213
#Sta/Elev= 30
       0 2457.94   115.3 2394.48   135.8 2384.77   148.4  2381.8   191.2 2357.69
   216.6 2339.19   229.2 2312.87     240  2296.2   246.1 2291.16   258.8 2290.79
   290.6 2279.66   368.5 2285.34   402.2 2282.54   445.3 2284.96   469.7 2284.74
   482.4 2281.59   503.5 2283.42   527.5 2279.04   583.7  2278.2  585.362278.707
   604.8 2281.01   613.2 2284.91   634.9 2302.63   659.6 2327.34   663.8 2328.75
   684.9 2329.09   710.3 2334.41   770.7 2341.05   887.5 2369.66     951 2382.42
#Mann= 7 ,-1,0
       0      .1       0     240    .025       0     330      .1       0
   527.5    .045       0  585.36      .1       0     650     .06       0
     750      .1       0
Bank Sta=527.5,585.36
XS Rating Curve= 0 ,0
Exp/Cntr(USF)=0,0
Exp/Cntr=0.3,0.1

Type RM Length L Ch R = 1 ,15598   ,703.9,703.9,703.9
XS GIS Cut Line= 4
2211430.46367418558305.5328959232211644.76179287558242.577923192
2211998.96326818558163.6156059642212303.39109046557988.429497655
#Sta/Elev= 30
       0 2460.85    93.5 2404.06   114.3 2387.47   126.9 2383.71   172.5  2352.1
   181.1 2344.36   189.4 2334.01   206.1 2305.25   210.2 2296.24   214.4 2290.12
   222.7  2289.5   239.1 2283.06   251.4 2282.72   259.6 2278.58   266.5 2277.81
   374.8 2277.83   378.5 2278.13   388.2 2284.86   413.6 2286.18   458.6 2283.85
  466.852278.931   542.4 2277.85   549.1 2279.28   571.1 2305.22   587.6 2316.37
   612.4 2317.31   624.6 2322.86     643 2326.84   767.6 2344.46   937.5 2374.91
#Mann= 5 ,-1,0
       0      .1       0  466.85    .045       0   549.1      .1       0
  656.25     .06       0  746.25      .1       0
Bank Sta=466.85,549.1
XS Rating Curve= 0 ,0
Exp/Cntr=0.3,0.1

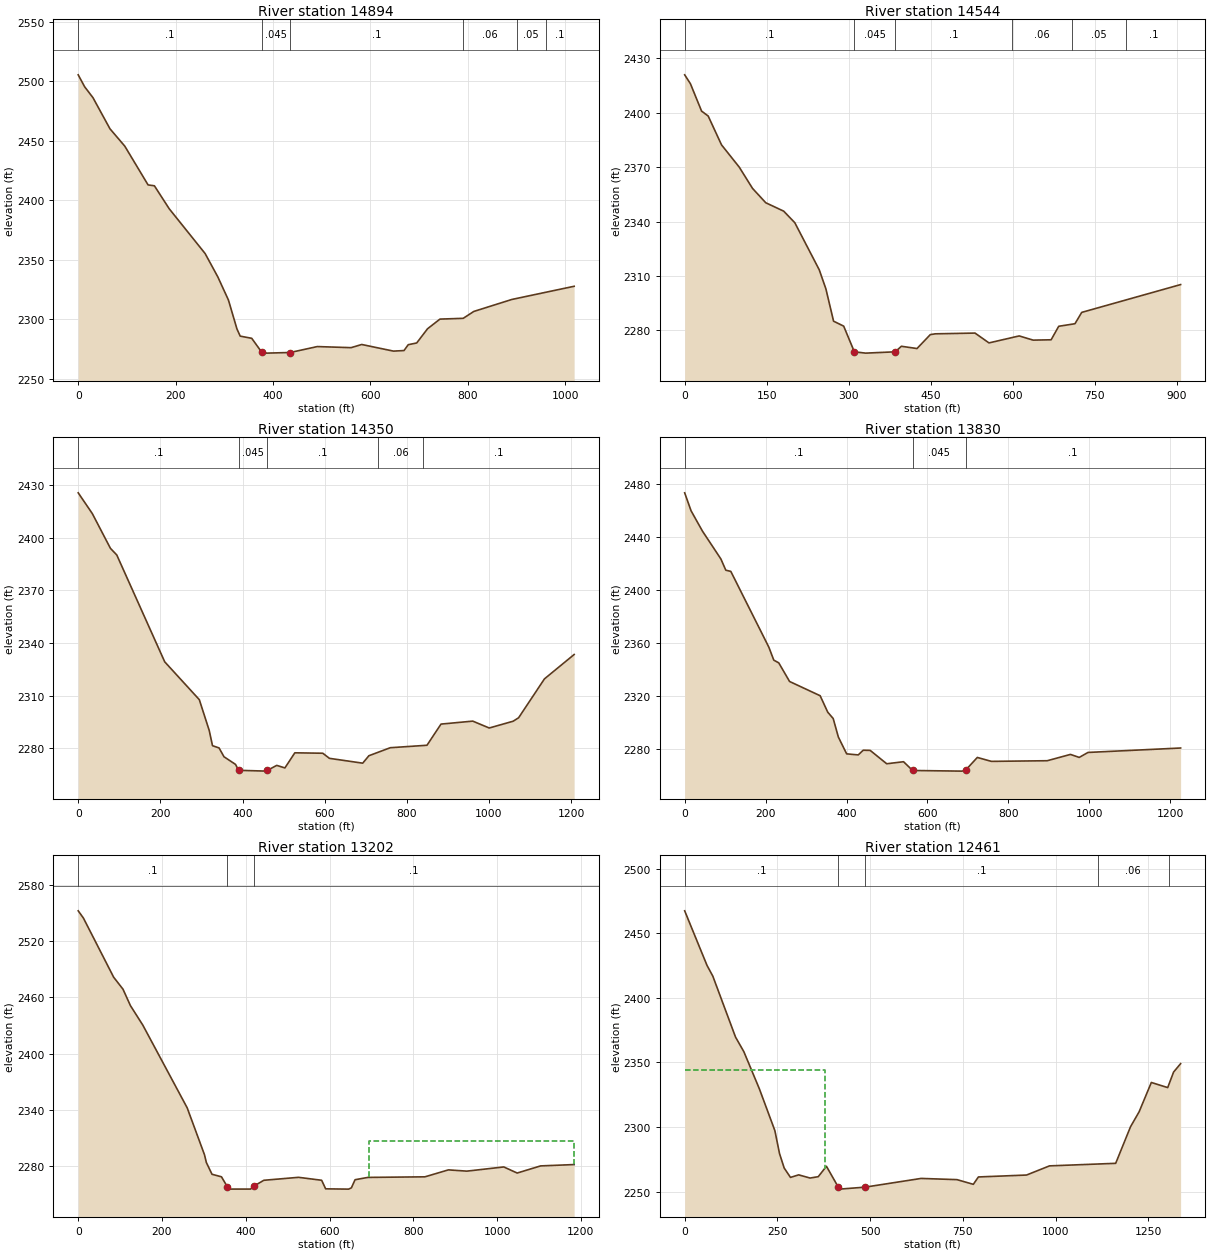
Type RM Length L Ch R = 1 ,14894   ,349,349,349
XS GIS Cut Line= 2
 2211528.0984722559044.7508666092212465.96373199558648.494142453
#Sta/Elev= 30
       0 2505.52    13.1 2495.54    30.3  2486.3    65.2 2460.13    95.6 2445.55
   143.4 2412.95   156.4 2412.21   186.8  2392.9   260.6  2355.2   286.7 2335.51
   308.4 2316.13   325.8 2291.92   332.5 2285.79   356.2 2283.95  376.952272.156
   386.6 2271.49  435.212272.016   490.8    2277   560.2 2276.09     582 2278.75
   647.1 2273.19   668.8 2273.64   677.5 2278.57   694.9 2280.04   717.1 2291.96
   742.6  2300.1   790.4 2300.75   812.1 2306.54   890.3 2316.63  1018.1 2327.71
#Mann= 6 ,-1,0
       0      .1       0  376.95    .045       0  435.21      .1       0
     790     .06       0     900     .05       0     960      .1       0
Bank Sta=376.95,435.21
XS Rating Curve= 0 ,0
Exp/Cntr(USF)=0,0
Exp/Cntr=0.3,0.1

Type RM Length L Ch R = 1 ,14544   ,194.1,194.1,194.1
XS GIS Cut Line= 3
2211669.79640601559274.8324821212212179.75156924559183.793080369
2212545.95416832559051.881071815
#Sta/Elev= 30
       0 2420.99    10.5 2416.09    30.9 2400.98      43 2398.27    67.4 2382.35
     100    2370   124.1 2358.34   148.3 2350.42   181.2 2345.76   201.5 2339.39
   246.2 2313.41   258.4 2302.85   272.4 2285.06   290.9 2282.34  310.41 2268.16
     331 2267.44   385.1 2268.16   396.5 2271.22     425 2269.97   449.4 2277.66
   458.6 2278.09   531.2  2278.5   556.7 2273.08     612 2276.93   637.5 2274.61
   670.4  2274.8   684.3 2282.25     714 2283.66   726.4 2289.92   907.3 2305.26
#Mann= 6 ,-1,0
       0      .1       0  310.41    .045       0   385.1      .1       0
  598.02     .06       0  708.02     .05       0  808.02      .1       0
Bank Sta=310.41,385.1
XS Rating Curve= 0 ,0
Exp/Cntr=0.3,0.1

Type RM Length L Ch R = 1 ,14350   ,520.5,520.5,520.5
XS GIS Cut Line= 3
2211625.94075983559431.5730717972212383.97818774559383.988588088
2212785.40280606559185.561599972
#Sta/Elev= 30
       0 2425.72    34.3 2413.89    78.4 2394.06    93.9 2390.25   210.6 2329.28
   294.8 2307.69   318.9 2290.15   326.9 2281.43   342.9 2280.14   354.9 2275.11
     383 2270.74  390.38 2267.37   459.1 2266.91  460.66 2267.34   483.3 2270.19
   503.2 2268.74   527.3 2277.36   595.4 2277.12   611.5 2274.21   692.6 2271.45
   707.6 2275.69   759.7 2280.27     849 2281.67   883.2 2293.75   960.5 2295.44
  1000.6 2291.52  1058.7 2295.38  1072.1 2297.36    1135 2319.55  1207.3 2333.46
#Mann= 5 ,-1,0
       0      .1       0  390.38    .045       0  460.66      .1       0
     730     .06       0  839.53      .1       0
Bank Sta=390.38,460.66
XS Rating Curve= 0 ,0
Exp/Cntr=0.3,0.1

Type RM Length L Ch R = 1 ,13830   ,628,628,628
XS GIS Cut Line= 3
2211552.76111207559740.5073199452211987.08616781559833.947770183
2212706.92371038560138.494422809
#Sta/Elev= 30
       0  2473.2    15.8 2459.69    43.8 2444.44    89.4 2423.45   101.7 2414.93
     114 2414.05   208.1 2356.96   220.3  2347.2   232.6 2345.16   259.3 2331.14
   334.9 2320.41   353.6 2308.05   367.1 2303.25   379.9 2289.29   400.4 2276.64
     429 2275.85   441.3 2279.37   458.5 2279.26   499.4 2269.19     541 2270.72
   563.5 2264.12   685.6 2263.64   694.8  2264.5   723.4 2273.94   758.2 2270.98
   896.2 2271.47   953.6 2276.22   975.3 2273.97     997 2277.71  1225.9 2281.04
#Mann= 3 ,-1,0
       0      .1       0   563.5    .045       0   694.8      .1       0
Bank Sta=563.5,694.8
XS Rating Curve= 0 ,0
Exp/Cntr(USF)=0,0
Exp/Cntr=0.3,0.1

Type RM Length L Ch R = 1 ,13202   ,741.5,741.5,741.5
XS GIS Cut Line= 4
2211417.18078108560155.9297099062211722.87966475560316.004852517
2211998.35640763560472.2043970362212520.11882017560451.387109971
#Sta/Elev= 30
       0 2552.25    12.4 2544.55    84.7 2481.38   106.9 2468.67   124.6 2451.17
   154.3 2430.28   260.1 2342.14   301.4 2292.12   305.9 2283.79   319.4 2271.22
     342 2268.52   355.7 2258.14   363.7 2255.42   411.4 2255.43   420.2 2258.81
   443.1 2264.81   525.9 2267.97   581.1 2264.83   590.7 2255.69   645.5 2255.38
   652.1 2256.73   660.9 2265.41   691.6 2267.88   827.7  2268.5   883.7 2275.91
   927.8 2274.57  1015.9 2279.04  1047.9 2272.54  1103.9 2280.15  1183.9 2281.58
#Mann= 3 ,-1,0
       0      .1       0   355.7    .045       0   420.2      .1       0
#XS Ineff= 2 , 0
                          693.69          2307.2
Permanent Ineff=
       F       F
Bank Sta=355.7,420.2
XS Rating Curve= 0 ,0
Exp/Cntr=0.3,0.1

Type RM Length L Ch R = 1 ,12461   ,561.3,561.3,561.3
XS GIS Cut Line= 5
2211061.59253663560392.6190559792211143.09458447560660.335794095
2211219.65572011560826.5476399472211402.87472595561227.881872751
2211421.74952079561660.038260776
#Sta/Elev= 30
       0 2467.46    60.2 2425.18    75.8 2416.89   137.1 2369.62   159.5 2358.31
   201.3 2329.55   243.1 2297.16   255.6  2279.4   268.2 2268.17   285.2 2260.92
   307.2 2262.89     338 2260.43     360 2261.49   382.1 2269.54     414 2253.39
   417.3 2251.84   486.4 2253.38   637.2 2260.13   733.9 2259.19   777.9 2255.56
   791.6 2261.27   921.3 2262.75   983.2 2269.85  1161.6 2271.83  1201.6 2300.16
  1224.9 2311.84  1257.7 2334.47  1301.8 2330.51  1317.7 2342.55  1336.6 2349.05
#Mann= 5 ,-1,0
       0      .1       0     414    .045       0   486.4      .1       0
 1114.02     .06       0 1304.02      .1       0
#XS Ineff= 2 , 0
             377    2344
Permanent Ineff=
       F       F
Bank Sta=414,486.4
XS Rating Curve= 0 ,0
Exp/Cntr=0.3,0.1

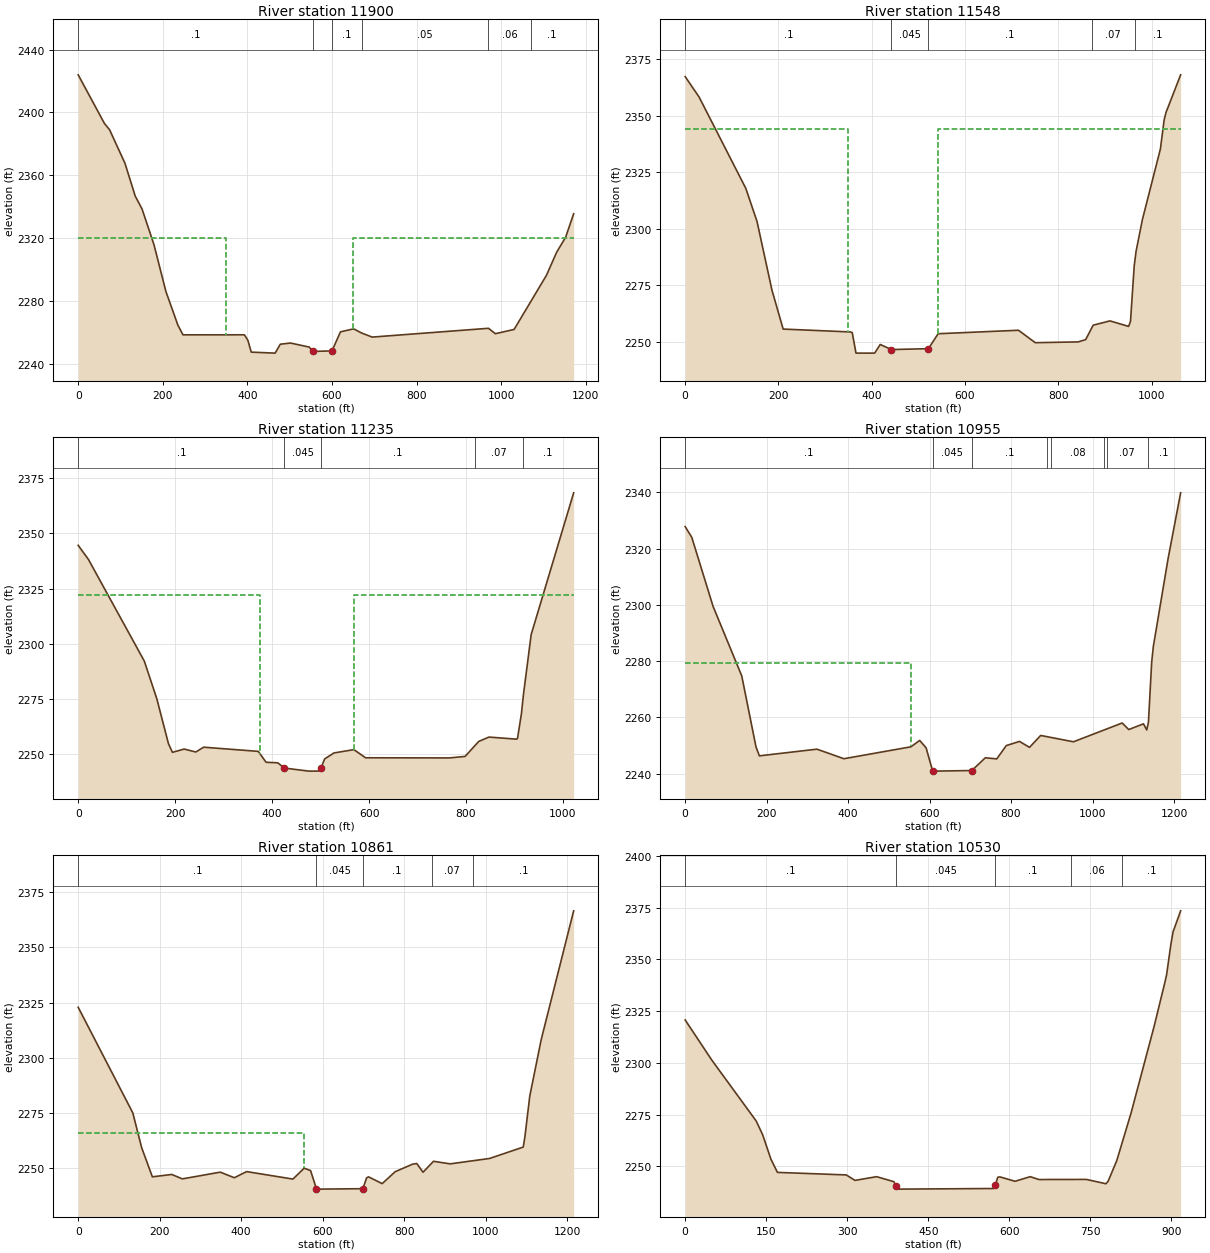
Type RM Length L Ch R = 1 ,11900   ,351.1,351.1,351.1
XS GIS Cut Line= 2
2210629.60888371560471.5448850182210783.42032443561632.821262457
#Sta/Elev= 30
       0 2423.94    62.2 2392.91    74.3 2388.93   110.6 2367.61   134.8 2346.73
   150.9 2338.54   179.2 2315.73   207.4 2285.92   235.7 2264.51   247.8 2258.31
     393 2258.33   401.1 2254.89   409.2 2247.29   465.7 2246.66   477.8 2252.34
     502 2253.09   546.4 2250.49   554.4 2247.75   600.12248.075   620.1 2260.23
   651.3 2262.12     670 2259.48     695 2256.88     970 2262.48   986.2 2259.03
  1030.6 2261.74  1107.2 2296.28  1131.4 2311.05  1152.4 2320.44  1171.4 2335.45
#Mann= 6 ,-1,0
       0      .1       0   554.4    .045       0   600.1      .1       0
     670     .05       0     970     .06       0    1070      .1       0
#XS Ineff= 2 , 0
             350    2320     650            2320
Permanent Ineff=
       F       F
Bank Sta=554.4,600.1
XS Rating Curve= 0 ,0
Exp/Cntr(USF)=0,0
Exp/Cntr=0.3,0.1

Type RM Length L Ch R = 1 ,11548   ,313.7,313.7,313.7
XS GIS Cut Line= 5
2210332.36443023560567.4764418782210345.24720673560773.844848454
     2210354.667      561058.3982210374.33183623 561439.87948225
2210381.84215619561628.533841747
#Sta/Elev= 30
       0 2367.27    29.8 2358.26     130 2317.83     154 2303.22   186.1 2272.77
   210.1 2255.57   354.2  2254.3   358.2 2254.01   366.2 2244.96   370.2 2244.93
   406.2 2244.93   418.2 2248.75   442.2 2246.51  521.532246.901   542.3 2253.51
   714.6 2255.05   750.6 2249.55   842.7  2249.9   858.7 2250.92   874.8  2257.3
   910.8 2259.19   950.8 2256.75   954.8    2259   962.8 2283.61   966.8 2290.04
   980.4  2304.1  1018.9 2335.25  1026.9 2348.08  1030.9 2351.39  1062.3 2368.06
#Mann= 5 ,-1,0
       0      .1       0   442.2    .045       0  521.53      .1       0
  871.48     .07       0  963.47      .1       0
#XS Ineff= 2 , 0
             350    2344  542.33            2344
Permanent Ineff=
       F       F
Bank Sta=442.2,521.53
XS Rating Curve= 0 ,0
Exp/Cntr=0.3,0.1

Type RM Length L Ch R = 1 ,11235   ,279.7,279.7,279.7
XS GIS Cut Line= 4
2210033.47245765560624.0893021292210011.74548674 560811.77252165
2210082.12114461561445.4481509182210091.54214031561640.761728536
#Sta/Elev= 30
       0 2344.59    21.2 2338.19   136.4 2292.17   162.2 2275.11   186.2 2254.79
   194.4 2250.85   218.5 2252.33   242.7    2251   258.8 2253.18   371.5 2251.28
   387.6 2246.35   411.7  2246.1   425.5 2243.72   476.1 2242.34   496.2 2242.36
  501.16 2243.94   508.3 2247.85   527.5 2250.57   568.7 2252.08   592.8 2248.38
   765.9 2248.32   798.1    2249   826.2 2255.79   847.3 2257.76   904.6 2256.81
   906.3 2257.31   914.3 2268.38   918.3 2276.79   934.4  2304.2    1022 2368.37
#Mann= 5 ,-1,0
       0      .1       0   425.5    .045       0  501.16      .1       0
  818.94     .07       0  916.51      .1       0
#XS Ineff= 2 , 0
             375    2322  568.66            2322
Permanent Ineff=
       F       F
Bank Sta=425.5,501.16
XS Rating Curve= 0 ,0
Exp/Cntr=0.3,0.1

Type RM Length L Ch R = 1 ,10955   ,94.5,94.5,94.5
BEGIN DESCRIPTION:
structure
END DESCRIPTION:
XS GIS Cut Line= 6
2209348.73516289560683.1391834542209457.37997112560928.235353979
2209672.86272637561026.1820609092209916.50515986561368.995535164
2210002.20852842561431.5877131572210019.63639232561611.941081404
#Sta/Elev= 30
       0  2327.8    16.2    2324    68.4 2299.49   138.9 2274.72   173.9 2249.47
   182.2 2246.31   323.5 2248.69   389.6 2245.29   554.1 2249.52   575.7 2251.79
   591.5 2249.16  607.182241.098   608.8 2240.88   703.7 2241.09   736.8 2245.62
   764.9 2245.23   788.3 2249.96   820.7 2251.44   845.3 2249.33   872.7 2253.56
   953.3 2251.31  1072.8 2257.99  1088.9 2255.66  1125.1 2257.69  1133.1 2255.51
  1137.3 2258.35  1145.2 2279.63  1149.2 2285.12  1185.4 2316.35  1216.3 2339.81
#Mann= 8 ,-1,0
       0      .1       0  607.18    .045       0   703.7      .1       0
  887.46     .07       0  897.46     .08       0 1028.94      .1       0
 1035.06     .07       0 1135.06      .1       0
#XS Ineff= 2 , 0
          555.57  2279.2
Permanent Ineff=
       F       F
Bank Sta=607.18,703.7
XS Rating Curve= 0 ,0
Exp/Cntr(USF)=0,0
Exp/Cntr=0.3,0.1

Type RM Length L Ch R = 1 ,10861   ,330.2,330.2,330.2
BEGIN DESCRIPTION:
structure
END DESCRIPTION:
XS GIS Cut Line= 6
2209266.65586355560723.5415381052209375.30067178560968.637708629
2209590.78342703 561066.584415562209834.42586052561409.397889815
2209920.12922908561471.9900678072209937.55709298561652.343436055
#Sta/Elev= 30
       0 2322.84   134.1 2275.11   155.7 2259.46   182.1 2246.22   229.8 2247.29
   255.7 2245.29   348.7 2248.33   383.3 2245.81   413.5 2248.58   527.2  2245.2
   554.7 2250.13   570.5 2249.04   584.7 2240.87   589.5 2240.66  698.922240.855
     708 2245.75   712.7 2246.21   746.3 2243.15   778.3 2248.55   820.9 2251.94
   831.2 2252.23   846.6  2248.3   872.2 2253.24   913.3 2252.08    1010 2254.52
  1092.5 2259.66  1096.5 2264.15  1108.6 2282.72  1136.7 2308.27  1216.3 2366.43
#Mann= 5 ,-1,0
       0      .1       0   584.7    .045       0  698.92      .1       0
  867.46     .07       0  968.94      .1       0
#XS Ineff= 2 , 0
          554.78 2266.21
Permanent Ineff=
       F       F
Bank Sta=584.7,698.92
XS Rating Curve= 0 ,0
Exp/Cntr(USF)=0,0
Exp/Cntr=0.3,0.1

Type RM Length L Ch R = 1 ,10530   ,480.9,480.9,480.9
XS GIS Cut Line= 4
 2209259.7736493 560740.746134022209344.92450569560936.340409737
 2209369.5206207 561511.797149242209359.40642119561639.063261148
#Sta/Elev= 30
       0 2320.69    49.3  2301.3   131.4  2271.9   143.5 2265.17   158.7 2253.43
   170.8 2247.04   298.2 2245.81   314.3 2243.17   354.3 2244.97   386.3 2242.55
     390 2240.39   394.3 2238.95   570.5 2239.25   574.3 2241.07   578.5 2244.68
   582.5 2244.86   610.5 2242.74   638.6 2244.97   654.6 2243.59   742.6 2243.64
   778.7 2241.55   782.7 2242.72   798.7 2252.66   825.3 2275.78   867.8 2317.49
     887 2337.96     891 2342.52     899 2357.33     903 2363.31     917 2373.44
#Mann= 5 ,-1,0
       0      .1       0     390    .045       0   574.3      .1       0
  713.33     .06       0  809.31      .1       0
Bank Sta=390,574.3
XS Rating Curve= 0 ,0
Exp/Cntr=0.3,0.1