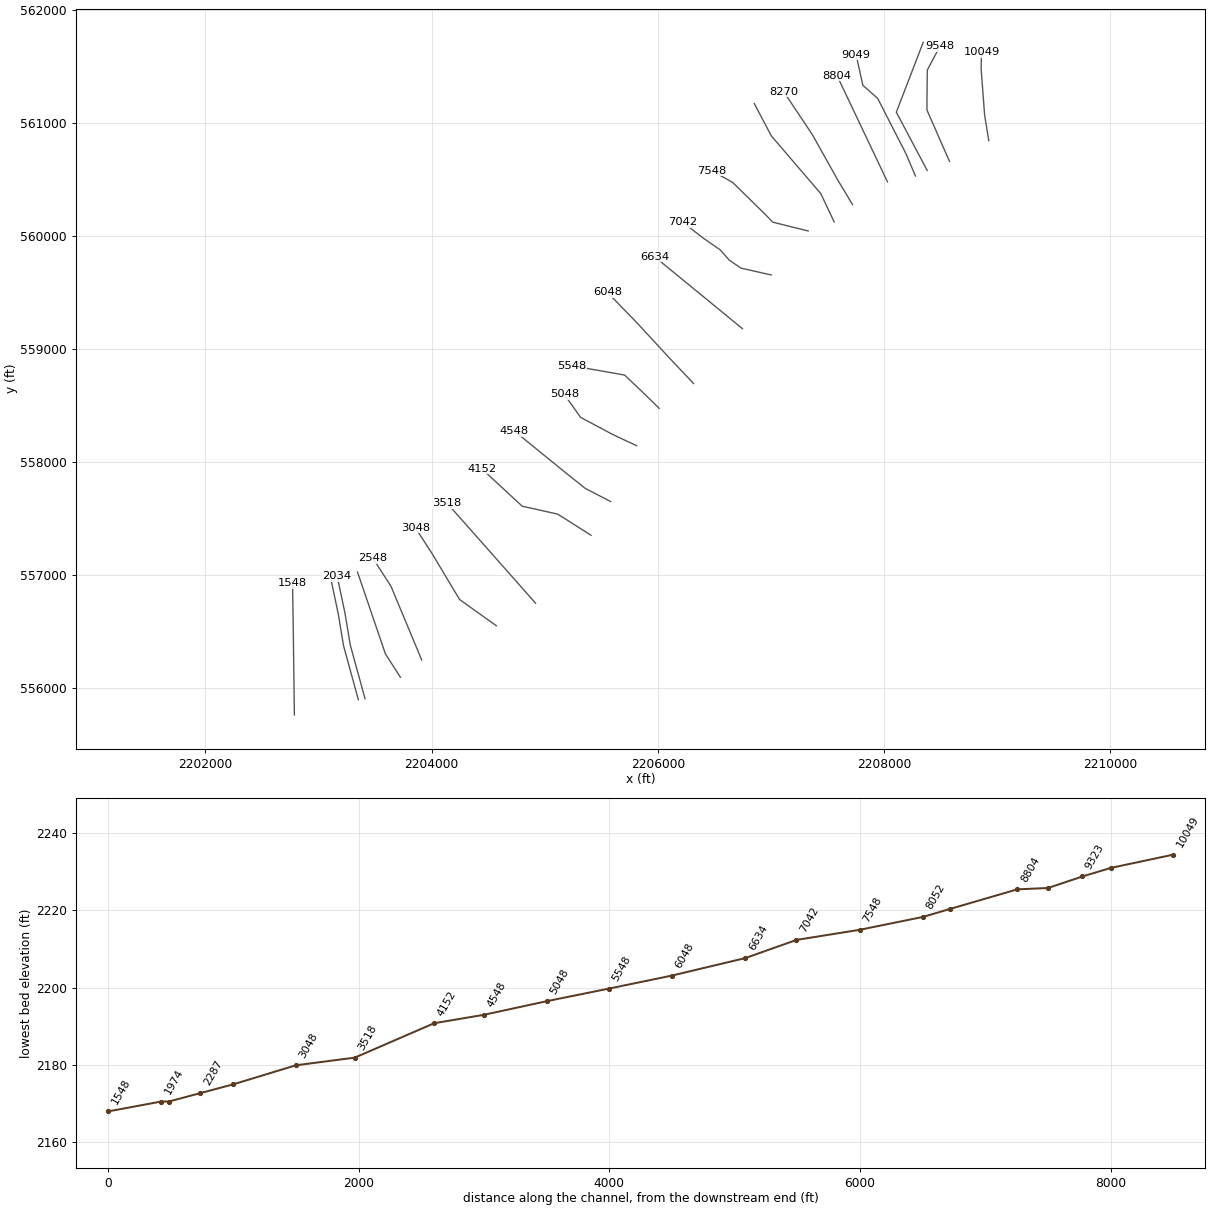
HEC-RAS study ELKRIV.prj: ELKRIV

--- ELKRIV.g01 (geometry) --- (continued)

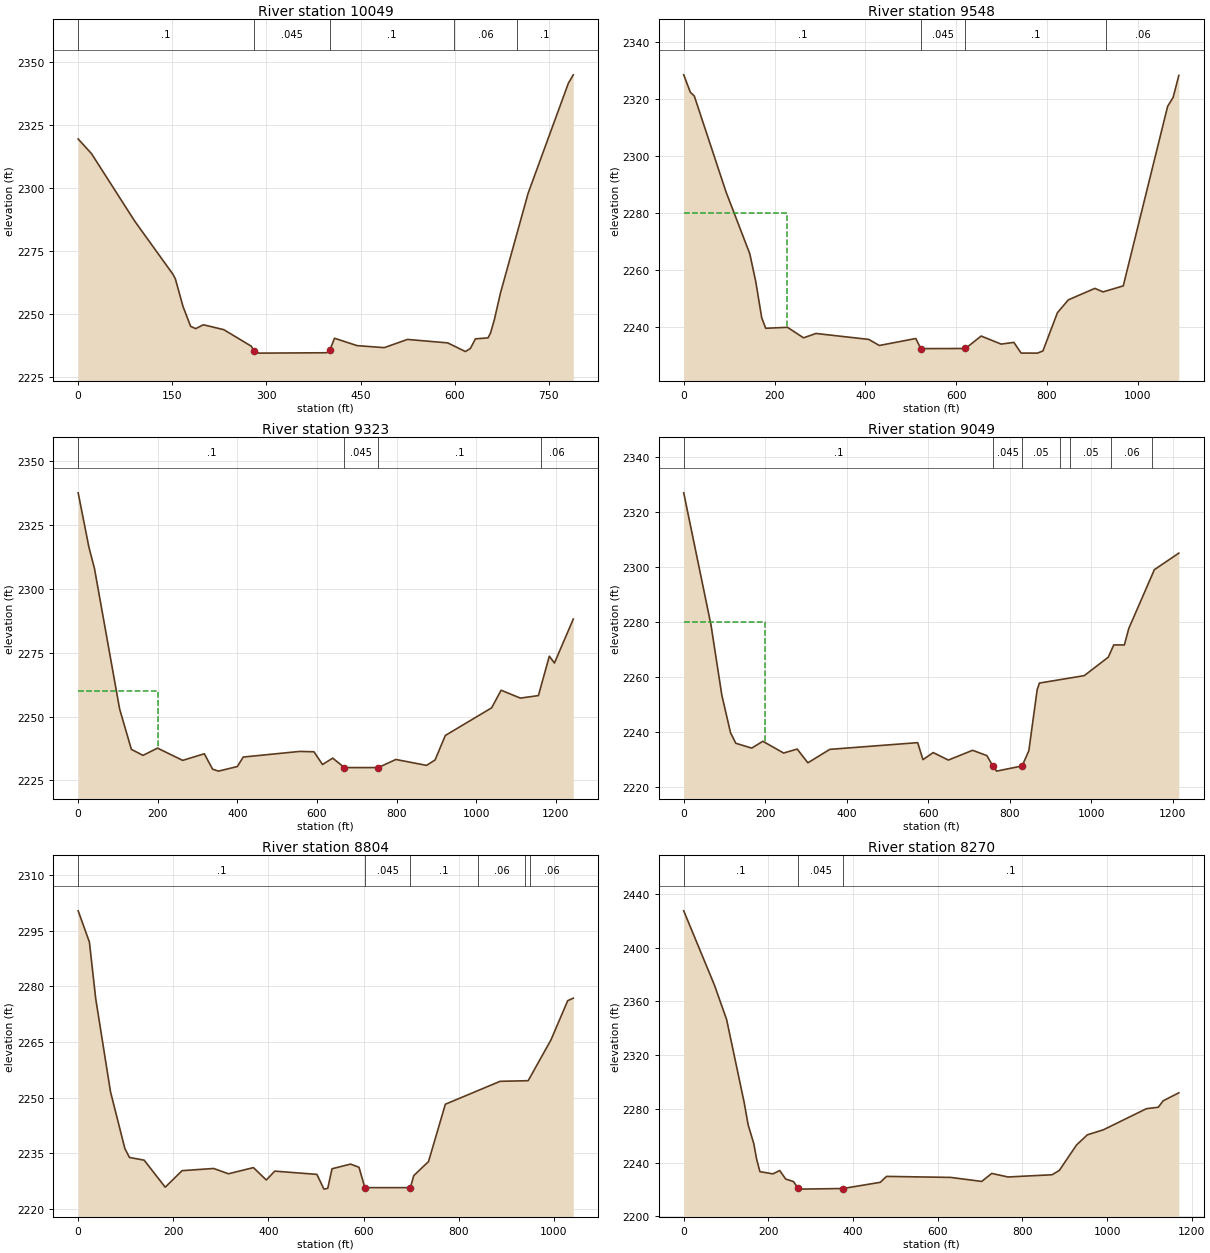
Type RM Length L Ch R = 1 ,10049   ,501.1,501.1,501.1
XS GIS Cut Line= 4
2208925.34720026560840.2938708252208888.65333358561066.489784926
2208857.54803395561475.7156353392208860.97322208 561625.04043619
#Sta/Elev= 30
       0 2319.49    21.2 2313.68      90 2286.85   150.8 2265.75   154.9 2263.83
     167  2252.9   179.2 2244.96   187.3 2244.06   199.5 2245.59   232.1 2243.64
     276 2237.04     280 2235.29     288 2234.31   396.1 2234.46  401.382235.699
   408.4 2240.23   444.5 2237.29   487.7 2236.49   524.7 2239.76   588.9 2238.38
     617 2234.94     625 2236.18     633 2239.99     653 2240.37     657 2242.26
   663.1 2247.57     673 2258.33     717 2297.94   781.1 2341.68   788.9 2345.01
#Mann= 5 ,-1,0
       0      .1       0     280    .045       0  401.38      .1       0
  599.15     .06       0  699.56      .1       0
Bank Sta=280,401.38
XS Rating Curve= 0 ,0
Exp/Cntr(USF)=0,0
Exp/Cntr=0.3,0.1

Type RM Length L Ch R = 1 ,9548    ,225.7,225.7,225.7
XS GIS Cut Line= 5
2208578.50878543560655.8088372452208379.01147196561110.730451895
     2208378.677      561186.2722208381.80885895561464.733531688
2208494.07270995561676.665681262
#Sta/Elev= 30
       0 2328.53    14.6 2322.41    23.3  2321.1    93.2 2287.43   145.5 2265.75
   158.7 2255.94   171.8 2243.28   180.6 2239.58   228.6 2239.92   263.9 2236.23
   291.3 2237.76   407.7 2235.67   430.9 2233.54   511.2 2235.99  522.292232.443
  620.562232.485   655.2 2236.86   699.2 2234.03   727.2 2234.63   743.2 2230.88
   779.2 2230.86   791.2 2231.63   823.2 2245.05   847.2 2249.55   905.6 2253.58
   923.7 2252.35   968.2 2254.46  1065.9 2317.46    1078 2320.59  1090.6 2328.32
#Mann= 4 ,-1,0
       0      .1       0  522.29    .045       0  620.56      .1       0
  930.76     .06       0
#XS Ineff= 2 , 0
             227    2280
Permanent Ineff=
       F       F
Bank Sta=522.29,620.56
XS Rating Curve= 0 ,0
Exp/Cntr=0.3,0.1

Type RM Length L Ch R = 1 ,9323    ,273.6,273.6,273.6
XS GIS Cut Line= 3
2208380.83139384560577.0763301862208107.86355923561092.154765932
2208345.22689367561709.299435489
#Sta/Elev= 30
       0 2337.59      27 2316.31    40.9 2308.03   104.2 2252.97   133.7 2237.18
   163.1 2234.83   199.3 2237.67   262.7 2232.87     317 2235.45   337.9 2229.41
   352.7 2228.66     400 2230.46   414.8 2234.17   556.6 2236.37   592.6 2236.23
     614 2231.25   639.7 2233.75  668.952230.042   754.2 2230.05   798.3 2233.22
   875.5 2230.91   896.9 2233.02   922.6 2242.61    1039 2253.43  1062.9 2260.32
  1111.2 2257.24  1156.6 2258.23    1184 2273.65  1196.9 2270.97  1244.2 2288.18
#Mann= 4 ,-1,0
       0      .1       0  668.95    .045       0   754.2      .1       0
 1162.94     .06       0
#XS Ineff= 2 , 0
             200    2260
Permanent Ineff=
       F       F
Bank Sta=668.95,754.2
XS Rating Curve= 0 ,0
Exp/Cntr(USF)=0,0
Exp/Cntr=0.3,0.1

Type RM Length L Ch R = 1 ,9049    ,245.2,245.2,245.2
XS GIS Cut Line= 5
2208277.26217578560527.5712791582208193.24150303560725.057320228
2207943.13034743561214.1499879212207812.12430917 561330.13473599
2207752.21317434 561599.76568601
#Sta/Elev= 30
       0 2327.11      67  2278.9    93.5 2253.39   114.8 2239.74   127.8 2235.84
   166.9 2234.08   194.2 2236.57   245.2 2232.28   278.5 2233.73   304.7 2228.72
   358.5 2233.62   574.2 2236.07   587.1 2229.88   612.3 2232.45   649.5 2229.72
     709 2233.28   744.1 2231.34  758.712227.522   767.9 2225.69   830.5 2227.58
     847 2233.12   867.4 2255.36     873 2257.78     983 2260.49    1042 2267.22
  1055.4 2271.69  1081.4 2271.67  1092.3 2277.68  1155.1 2299.11  1215.1 2305.14
#Mann= 7 ,-1,0
       0      .1       0  758.71    .045       0   830.5     .05       0
  923.95     .06       0  948.92     .05       0 1048.92     .06       0
 1148.92      .1       0
#XS Ineff= 2 , 0
             200    2280
Permanent Ineff=
       F       F
Bank Sta=758.71,830.5
XS Rating Curve= 0 ,0
Exp/Cntr=0.3,0.1

Type RM Length L Ch R = 1 ,8804    ,534.1,534.1,534.1
XS GIS Cut Line= 2
2208029.57388195560475.8223849172207583.52648804561416.138512616
#Sta/Elev= 30
       0 2300.38    23.6 2291.97    36.9 2276.68    67.9 2251.63    98.2 2236.26
   107.8 2233.88   138.7 2233.15     183 2225.86   218.4 2230.32   284.8 2230.91
   315.8 2229.48   368.4 2231.14   395.5  2227.8   413.2 2230.19   501.8 2229.32
   516.6 2225.34   524.6 2225.56   533.6 2230.83   572.6 2232.09   590.3 2231.23
   602.6 2225.74  698.23 2225.74   705.4 2228.98   736.4 2232.77   771.8 2248.23
   886.9 2254.41   945.9 2254.58   993.8 2265.58    1029 2276.15  1040.7 2276.84
#Mann= 6 ,-1,0
       0      .1       0   602.6    .045       0  698.23      .1       0
     840     .06       0     940      .1       0     950     .06       0
Bank Sta=602.6,698.23
XS Rating Curve= 0 ,0
Exp/Cntr(USF)=0,0
Exp/Cntr=0.3,0.1

Type RM Length L Ch R = 1 ,8270    ,217.4,217.4,217.4
XS GIS Cut Line= 4
2207720.96785273560274.847341094  2207591.202066 560490.25997736
2207366.61673483560892.0246984892207112.60656404561273.001990544
#Sta/Elev= 30
       0 2427.38    72.8 2371.94   101.4 2346.44   142.8 2284.81   152.2 2268.12
   165.5 2254.21   172.1 2242.77     180 2233.31   210.8 2231.66   226.7 2234.19
   240.9  2227.8   259.4 2225.92   270.5 2220.84   273.5 2220.31   376.4 2220.77
   464.5 2225.39     479 2229.78   630.6 2229.03   703.9 2226.04   727.6 2231.99
     766 2229.35   870.1    2231   887.4 2234.26   927.8  2253.1   953.5 2260.72
   991.3 2264.45  1092.9 2280.14  1121.1 2281.25  1132.6 2286.04  1169.6 2291.98
#Mann= 3 ,-1,0
       0      .1       0   270.5    .045       0   376.4      .1       0
Bank Sta=270.5,376.4
XS Rating Curve= 0 ,0
Exp/Cntr=0.3,0.1

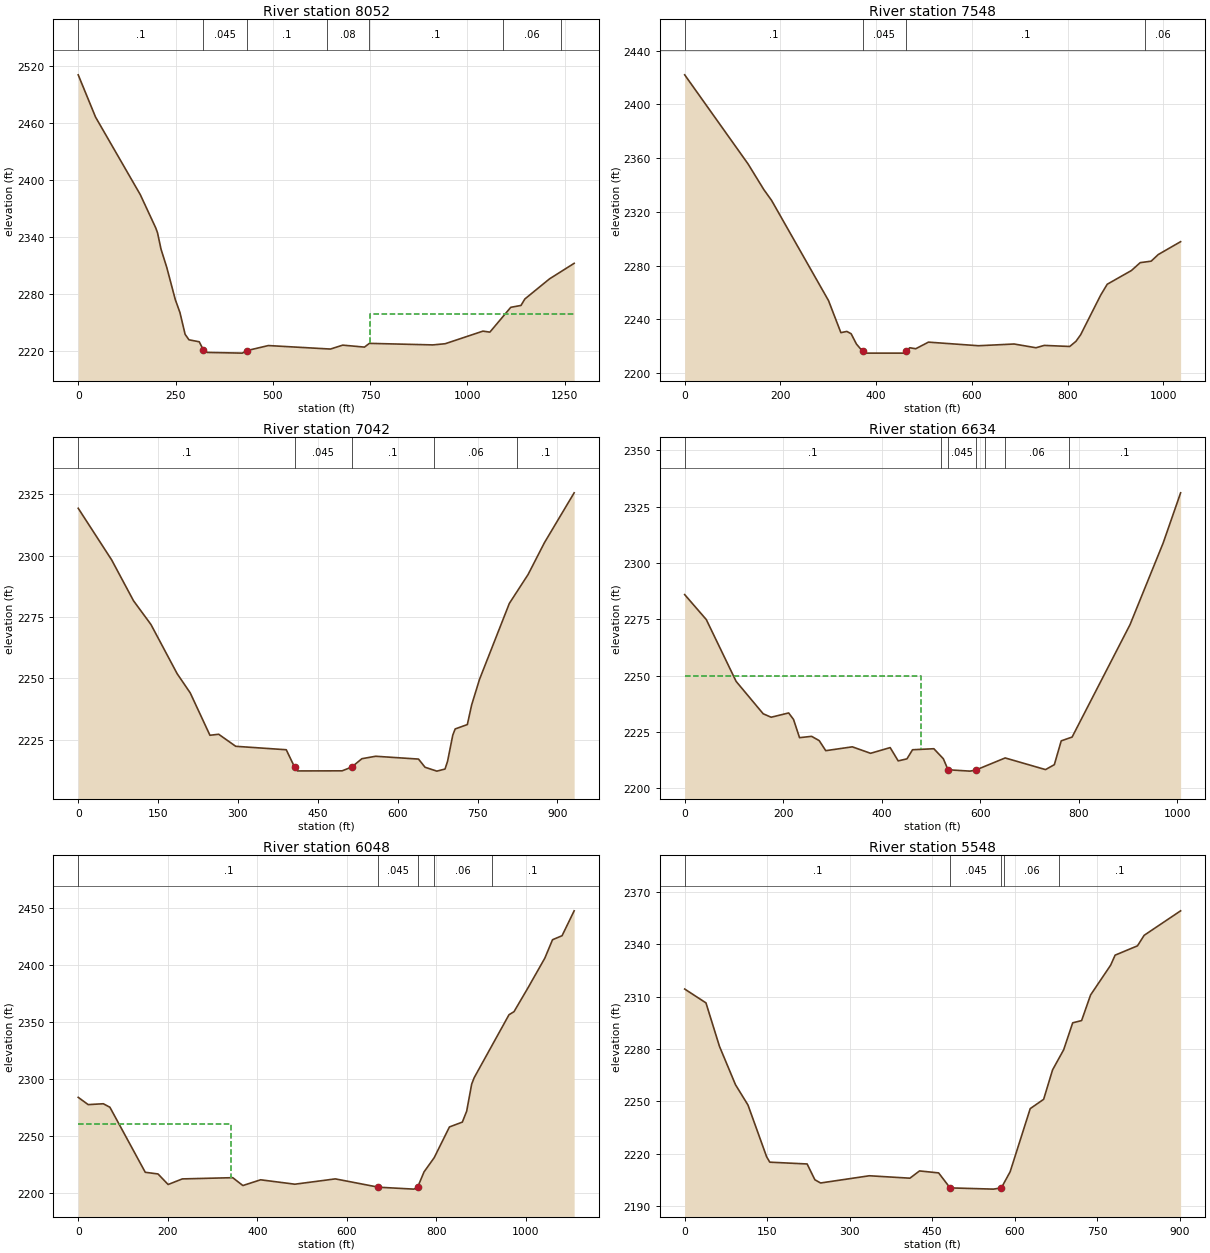
Type RM Length L Ch R = 1 ,8052    ,504,504,504
XS GIS Cut Line= 4
2207558.79939253560120.9046095362207439.95394568560372.171010024
2207002.47603505560883.0382265472206851.70165126 561169.20928278
#Sta/Elev= 30
       0 2510.69    44.6 2466.23   159.6 2384.67   199.4 2349.62   203.8 2344.59
   212.7 2327.51   227.5 2308.29   249.4 2274.48   261.4 2260.82   274.6 2238.03
   284.5 2232.23   310.9 2230.15   321.4 2221.76   331.9 2218.96   421.5 2218.23
   434.5 2220.98   488.4 2226.19   647.9 2222.51   679.5 2226.63   735.3 2224.56
     748 2228.49   911.1 2226.87   942.8 2228.12  1039.7 2241.35  1057.5  2240.3
  1111.2 2266.37  1137.4 2268.34  1147.4 2275.15  1210.7 2296.27    1274  2312.6
#Mann= 7 ,-1,0
       0      .1       0   321.4    .045       0   434.5      .1       0
  637.96     .08       0  747.96      .1       0 1090.54     .06       0
 1240.54      .1       0
#XS Ineff= 2 , 0
                          749.52         2259.86
Permanent Ineff=
       F       F
Bank Sta=321.4,434.5
XS Rating Curve= 0 ,0
Exp/Cntr=0.3,0.1

Type RM Length L Ch R = 1 ,7548    ,506.7,506.7,506.7
XS GIS Cut Line= 5
2207328.61234278560041.743262623 2207015.0960113560119.351325522
     2206949.124      560188.149 2206660.5172993560471.289674738
2206474.61682681 560576.11954648
#Sta/Elev= 30
       0 2422.07   132.3 2355.79   165.3 2336.67   181.6 2328.56   300.5    2254
   326.3 2230.16   338.8 2231.06   347.7 2229.34   358.8 2221.67   371.6 2216.32
   379.2 2214.91   458.9 2214.91  462.962216.284   470.1 2218.91   482.6 2218.17
   509.3 2223.09     614 2220.41   688.2  2221.7   733.9 2218.91     751 2220.66
   804.4 2219.86   817.5 2223.75   827.2 2228.62   868.9 2258.01   882.7 2266.19
   933.2 2276.39   951.6 2282.26   974.5 2283.36   989.3  2288.3    1036 2297.87
#Mann= 4 ,-1,0
       0      .1       0   371.6    .045       0  462.96      .1       0
   962.6     .06       0
Bank Sta=371.6,462.96
XS Rating Curve= 0 ,0
Exp/Cntr=0.3,0.1

Type RM Length L Ch R = 1 ,7042    ,407.7,407.7,407.7
XS GIS Cut Line= 6
2207001.39871297559652.4330634162206734.43207316559713.041191267
2206631.16981967559783.2293236792206551.88994421559873.770528122
2206399.85515863 559979.122737042206219.97656106560118.316113093
#Sta/Elev= 30
       0 2319.23    62.8 2298.22   103.8 2281.62   136.6 2271.94   185.8 2251.93
   210.4  2244.1   247.4 2226.87   263.8 2227.28   295.8 2222.38   390.7 2220.98
   406.5 2213.86   411.8 2212.36   495.7  2212.4  513.672213.938   532.7 2217.33
   558.6 2218.33   639.1 2217.18   651.4 2213.85   673.6 2212.28   688.9 2213.13
   693.7 2216.32   703.5 2226.96     708 2229.45   730.8 2231.22   738.9 2239.22
   753.6 2249.58   809.7 2280.52   844.9 2292.28   875.5 2305.19   931.4 2325.51
#Mann= 5 ,-1,0
       0      .1       0   406.5    .045       0  513.67      .1       0
  668.96     .06       0  823.93      .1       0
Bank Sta=406.5,513.67
XS Rating Curve= 0 ,0
Exp/Cntr=0.3,0.1

Type RM Length L Ch R = 1 ,6634    ,585.6,585.6,585.6
XS GIS Cut Line= 2
2206747.43216329559177.3698515412205968.76174464559815.687330531
#Sta/Elev= 30
       0 2285.94    43.9 2274.86   104.5 2247.41   159.4 2233.05   175.6 2231.52
   211.1 2233.42     221 2230.54   233.2 2222.45   257.7 2223.04   273.2 2221.13
   286.4 2216.68   340.4 2218.38   377.4 2215.51   417.2 2218.04   433.5 2212.14
   451.3 2213.05   462.6 2217.09   505.9 2217.54   525.2 2213.08  534.652208.202
   579.2  2207.6   590.5 2208.04   650.7 2213.45   732.6 2208.28   750.5 2210.46
   764.5 2221.04   786.6 2222.72   904.2 2272.61   971.4  2308.8  1006.9 2331.11
#Mann= 7 ,-1,0
       0      .1       0     520     .07       0  534.65    .045       0
   590.5     .07       0     610      .1       0     650     .06       0
     780      .1       0
#XS Ineff= 2 , 0
          479.59  2249.6
Permanent Ineff=
       F       F
Bank Sta=534.65,590.5
XS Rating Curve= 0 ,0
Exp/Cntr(USF)=0,0
Exp/Cntr=0.3,0.1

Type RM Length L Ch R = 1 ,6048    ,500.7,500.7,500.7
XS GIS Cut Line= 4
2206315.56160882558692.5313906122206100.62167619 558918.91216494
     2205828.266      559214.5882205554.64055812559497.852732581
#Sta/Elev= 30
       0 2283.75    22.3 2277.35    56.1 2278.11    70.8 2275.05   149.8 2217.89
   178.3 2216.41   200.9 2207.14   232.6 2212.06   345.2 2213.14   367.9 2206.23
   407.5 2211.28     484 2207.41   574.5 2212.08   670.8 2204.77     750 2203.08
   758.5 2204.93   772.6 2218.21   795.3  2230.7   829.4 2257.73   858.2 2261.99
   867.9  2271.6     879 2295.28   884.6 2300.99   962.5 2356.37   973.6 2359.02
  1004.6 2379.79  1042.5 2406.08  1059.7 2422.26    1081 2425.79    1108 2447.66
#Mann= 5 ,-1,0
       0      .1       0   670.8    .045       0   758.5     .07       0
  794.16     .06       0  924.16      .1       0
#XS Ineff= 2 , 0
          342.44    2260
Permanent Ineff=
       F       F
Bank Sta=670.8,758.5
XS Rating Curve= 0 ,0
Exp/Cntr=0.3,0.1

Type RM Length L Ch R = 1 ,5548    ,499.3,499.3,499.3
XS GIS Cut Line= 5
2206010.63906582558472.9076911422205881.86020829558599.195705777
2205705.86847793558766.7555461752205610.57568708558783.834312922
2205234.94957117558849.832692289
#Sta/Elev= 30
       0 2314.43    38.7 2306.49    63.2 2281.62    92.4 2259.57   115.1 2247.93
     149 2218.26   154.7 2215.18   222.6 2214.15   236.7  2205.1   247.1 2203.25
   335.7 2207.39   409.5    2206   426.9 2210.16   461.7 2209.03   482.5 2200.44
   561.4 2199.73  575.71 2200.45   591.7  2209.7   628.2 2245.88   652.6 2251.22
   668.8 2268.08     689 2279.63   705.4 2295.07   721.6 2296.35   737.9 2311.01
   774.4 2328.11   782.5 2333.84   823.2  2339.2   835.3 2345.22   901.6 2359.26
#Mann= 5 ,-1,0
       0      .1       0   482.5    .045       0  575.71      .1       0
  580.18     .06       0  680.18      .1       0
Bank Sta=482.5,575.71
XS Rating Curve= 0 ,0
Exp/Cntr=0.3,0.1

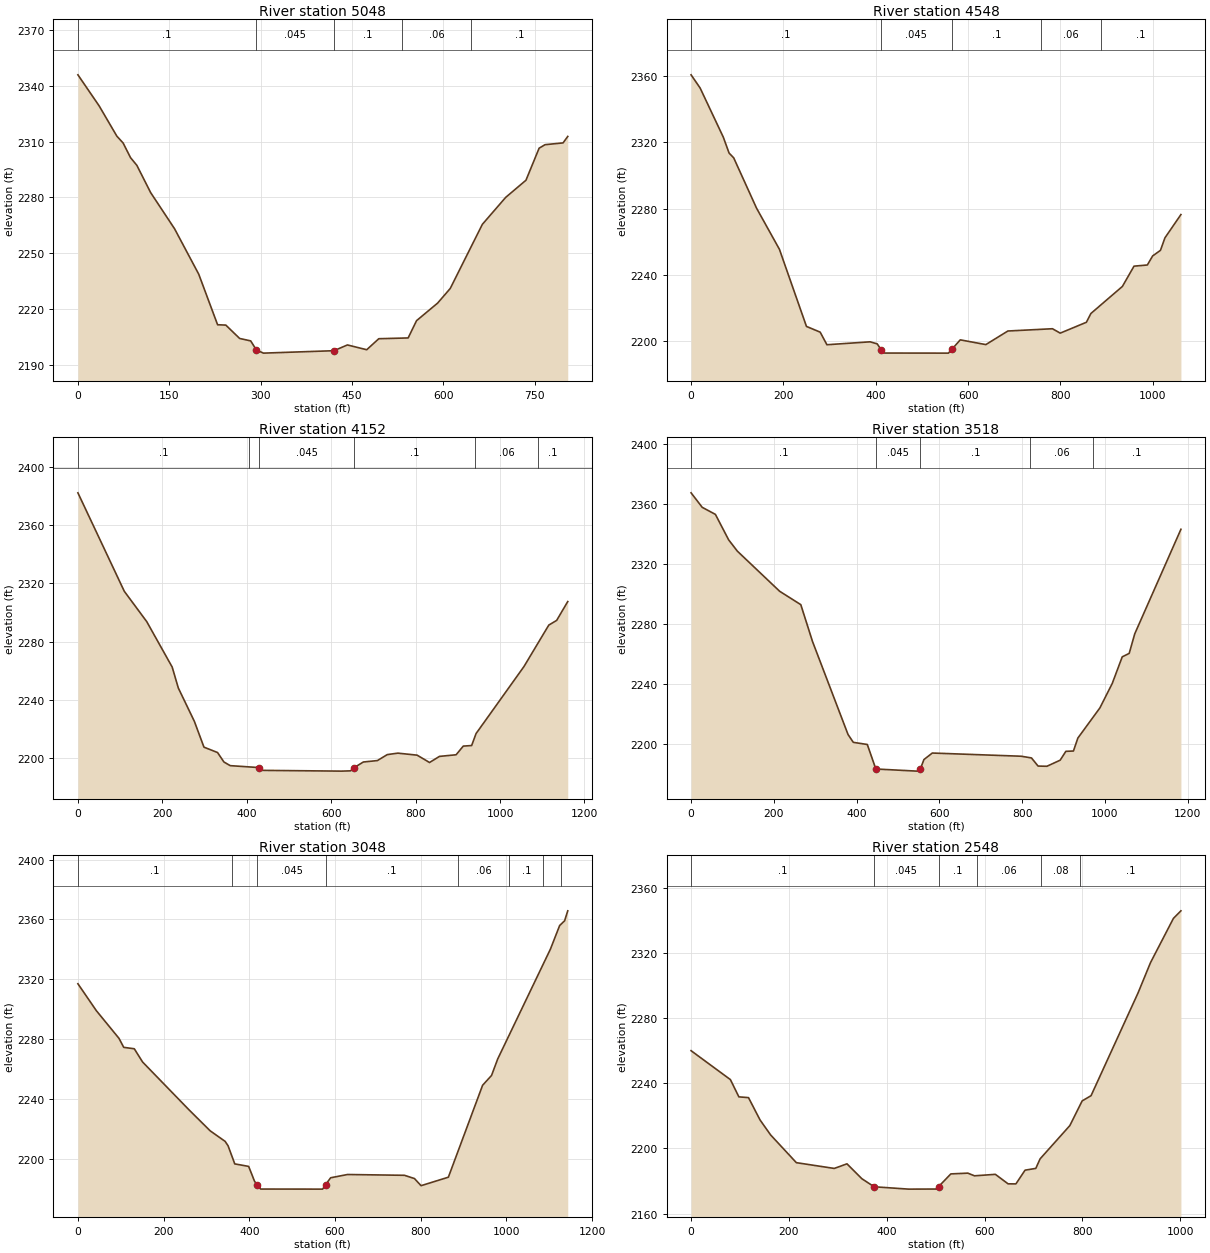
Type RM Length L Ch R = 1 ,5048    ,500,500,500
XS GIS Cut Line= 5
2205811.84707237558142.0604208372205599.27467579558241.650041472
     2205478.194       558306.542205316.66020902 558392.49093721
2205172.42623986558595.512031708
#Sta/Elev= 30
       0  2345.8      35 2329.07    63.9 2312.91    74.3 2309.18    86.3 2301.39
    96.8 2297.21   119.4 2282.61   158.7 2263.18   198.4 2238.79   229.3 2211.69
   242.8  2211.5   265.5 2204.33   283.6 2203.03     293 2198.16   304.6 2196.46
   420.3 2197.76   442.4 2200.85   474.1 2198.28   493.9 2204.19   542.1 2204.61
   555.9 2213.88   590.5 2223.31   611.2 2231.16   663.9 2265.56   702.2 2280.03
   735.5 2289.24   757.1 2306.43   766.9 2308.32   796.4 2309.27   804.1 2312.74
#Mann= 5 ,-1,0
       0      .1       0     293    .045       0   420.3      .1       0
  532.12     .06       0  645.09      .1       0
Bank Sta=293,420.3
XS Rating Curve= 0 ,0
Exp/Cntr=0.3,0.1

Type RM Length L Ch R = 1 ,4548    ,396.9,396.9,396.9
XS GIS Cut Line= 4
2205582.12153364 557648.190253872205358.17404445557764.089890862
     2205182.109      557904.6442204729.35851167558272.625302286
#Sta/Elev= 30
       0 2360.68    19.6 2352.74    69.8 2323.12    82.3 2313.53    92.3 2310.66
   141.8 2280.32   191.4  2255.5   249.9 2209.05   279.6  2205.6   294.2 2198.01
   387.8 2199.76   403.1 2198.54  411.45 2195.09   418.5    2193   557.3 2192.95
   564.5 2195.15     583 2200.95   638.4 2198.09   686.1 2206.28   782.7 2207.65
   799.5    2205   856.2 2211.55   865.9 2216.83   934.2 2233.16   959.3 2245.36
   988.2 2246.07   999.6 2251.51  1016.6  2254.9  1026.3 2262.44  1060.9 2276.46
#Mann= 5 ,-1,0
       0      .1       0  411.45    .045       0   564.5      .1       0
  757.45     .06       0  887.45      .1       0
Bank Sta=411.45,564.5
XS Rating Curve= 0 ,0
Exp/Cntr=0.3,0.1

Type RM Length L Ch R = 1 ,4152    ,633.7,633.7,633.7
XS GIS Cut Line= 5
 2205408.8417379557349.5789832092205159.07763523557508.742381973
2205108.87994793557538.1263940522204800.34782109557606.689088904
2204440.83328656557939.688800879
#Sta/Elev= 30
       0 2382.37   109.9 2314.58     163 2293.73   223.3 2262.44   237.9 2247.99
   275.9 2225.04   298.6 2207.29   330.8 2203.58   345.9 2197.08   360.8 2194.55
   428.8 2193.23     437  2191.3   625.2 2190.78     646 2190.98   654.2 2193.14
   676.1 2197.06   709.4 2198.04   732.9 2202.16   757.9 2203.16   803.6 2201.77
     833 2196.72   856.5 2200.92   895.9 2202.04   912.9 2208.01   932.7 2208.39
   943.2 2216.64  1056.7 2262.79  1115.5 2291.32  1134.1 2294.54  1160.4 2307.52
#Mann= 6 ,-1,0
       0      .1       0  404.33     .05       0   428.8    .045       0
   654.2      .1       0  940.39     .06       0 1090.39      .1       0
Bank Sta=428.8,654.2
XS Rating Curve= 0 ,0
Exp/Cntr(USF)=0,0
Exp/Cntr=0.3,0.1

Type RM Length L Ch R = 1 ,3518    ,469.4,469.4,469.4
XS GIS Cut Line= 2
2204918.26222587556749.126945114 2204134.2511322557635.678999267
#Sta/Elev= 30
       0  2367.3      27 2357.62    58.8 2352.94    90.8 2335.98   111.8 2328.45
     214 2301.72   265.1  2292.8   293.4 2268.27   379.2 2206.31     392 2201.07
   425.8 2199.64   446.4 2183.31   545.6 2181.89  553.522183.022   562.6 2189.59
   582.8 2193.94   797.8 2191.81   822.4 2190.68   838.4 2185.26   859.8 2185.13
   891.8 2189.19   905.5 2195.08   923.8 2195.28   934.5 2203.91   987.7 2223.99
  1017.6 2240.31  1041.7 2258.03  1058.5 2260.32  1071.9 2273.33  1183.5    2343
#Mann= 5 ,-1,0
       0      .1       0   446.4    .045       0  553.52      .1       0
     820     .06       0     970      .1       0
Bank Sta=446.4,553.52
XS Rating Curve= 0 ,0
Exp/Cntr(USF)=0,0
Exp/Cntr=0.3,0.1

Type RM Length L Ch R = 1 ,3048    ,500,500,500
XS GIS Cut Line= 5
2204571.24624742556549.4690231942204247.18493651556780.836596638
     2204189.424      556876.2842204006.52150084557182.907539155
2203856.11978299557415.168384945
#Sta/Elev= 30
       0 2317.05    43.1 2299.06    95.9  2280.6     107 2274.59   131.6 2273.64
   151.1 2264.77   259.3 2232.88   308.8 2218.84   343.7  2211.8   350.6 2208.84
   366.2 2196.77   398.6 2195.09   412.3  2185.2  418.982182.536   426.6 2179.97
   571.3 2179.92   578.4 2182.99     590  2187.5   629.3 2189.68   762.3 2189.15
   785.6 2186.99   801.1 2182.22   864.8 2187.88   944.7 2249.25   965.6 2255.83
     980 2266.84    1103 2340.14  1124.6 2355.94  1136.2 2359.12  1143.5 2365.75
#Mann= 8 ,-1,0
       0      .1       0     360    .025       0  418.98    .045       0
   578.4      .1       0  886.77     .06       0 1006.77      .1       0
 1086.77     .08       0 1126.77      .1       0
Bank Sta=418.98,578.4
XS Rating Curve= 0 ,0
Exp/Cntr=0.3,0.1

Type RM Length L Ch R = 1 ,2548    ,261.4,261.4,261.4
XS GIS Cut Line= 4
     2203911.397      556246.945     2203736.458      556666.971
2203640.31765511 556898.094022372203479.89774422557146.852320903
#Sta/Elev= 30
       0 2259.96    80.4 2242.21    97.7 2231.62   117.4 2231.15   141.1  2217.4
   162.7 2208.23   215.2 2191.24   292.7  2187.7   318.7 2190.52   349.1 2181.39
   374.3 2176.44   444.7    2175   500.7 2175.05   505.9 2176.53     531 2184.34
   565.7 2184.81   579.3 2183.17     622 2184.07     648 2178.25     664 2178.21
   682.7 2186.63   704.7 2187.73   713.4 2193.56   774.2 2213.98   799.4 2229.14
   817.6 2232.35   913.7 2295.42   939.1 2313.98     986 2341.16  1001.3 2345.79
#Mann= 6 ,-1,0
       0      .1       0   374.3    .045       0   505.9      .1       0
     585     .06       0  715.32     .08       0  795.32      .1       0
Bank Sta=374.3,505.9
XS Rating Curve= 0 ,0
Exp/Cntr=0.3,0.1

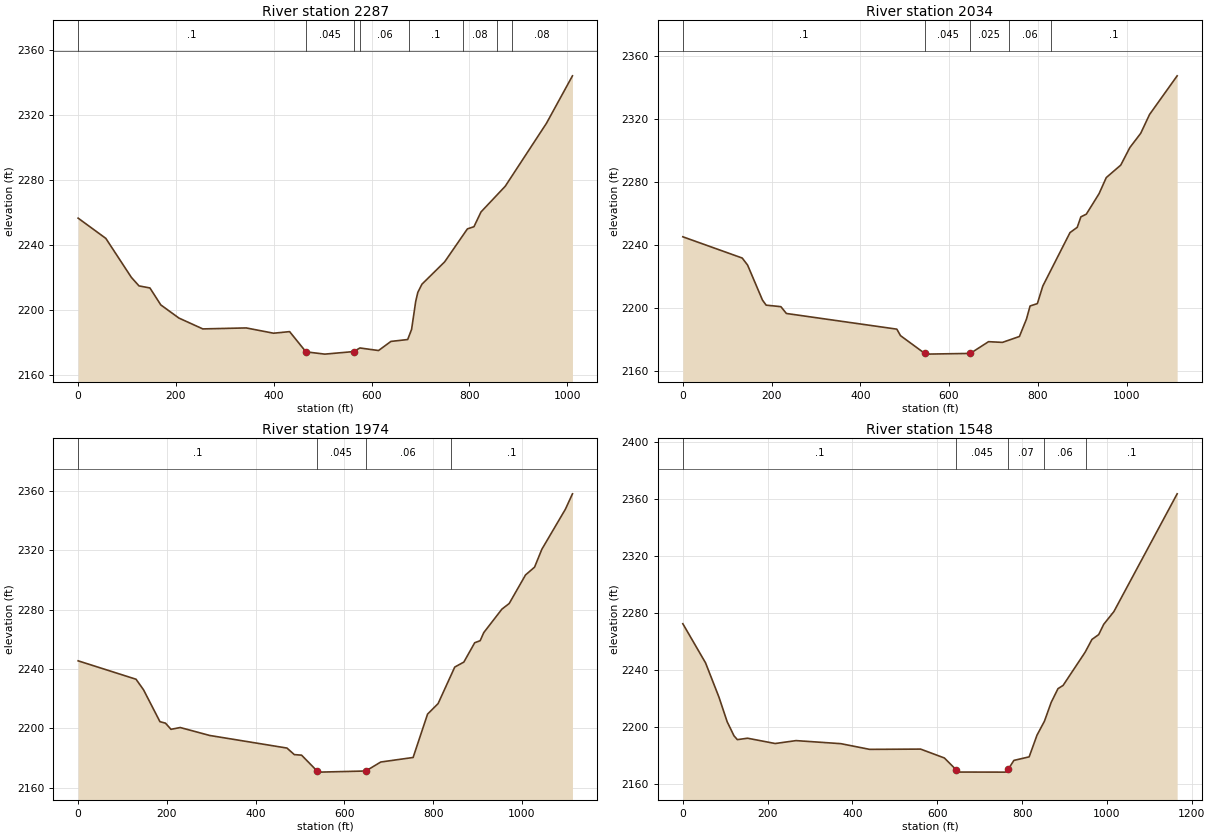
Type RM Length L Ch R = 1 ,2287    ,252.7,252.7,252.7
XS GIS Cut Line= 3
2203723.27560408556093.5313660552203590.57671749556300.873376359
2203343.83972523557024.496992321
#Sta/Elev= 30
       0 2256.42    56.6 2243.98   108.8 2219.99   124.5 2214.72   146.8 2213.46
     169 2203.04   206.1 2194.93   254.9 2188.26   343.7 2188.86   399.6 2185.61
   432.4 2186.59   465.8 2174.15   504.3 2172.74   563.5 2174.31   563.5 2174.32
   576.1 2176.53   614.2 2174.95   639.5 2180.56   673.8 2181.72   681.8 2187.98
   690.2 2205.18   694.5 2210.72   702.9 2215.76   749.4 2229.53   795.9 2249.82
   809.3 2251.15   823.7 2260.24   873.3 2276.07   957.4 2314.74  1010.7 2344.01
#Mann= 8 ,-1,0
       0      .1       0   465.8    .045       0   563.5    .025       0
  576.17     .06       0  676.17      .1       0  786.17     .08       0
  856.17      .1       0  886.17     .08       0
Bank Sta=465.8,563.5
XS Rating Curve= 0 ,0
Exp/Cntr(USF)=0,0
Exp/Cntr=0.3,0.1

Type RM Length L Ch R = 1 ,2034    ,60,60,60
BEGIN DESCRIPTION:
structure
END DESCRIPTION:
XS GIS Cut Line= 4
2203410.45767894555904.0569163542203279.71889438556380.571864469
2203233.01227378556662.0542548392203163.94069446556989.541101072
#Sta/Elev= 30
       0  2245.2   133.9 2231.68     146 2227.19   179.5 2204.94   187.8 2201.71
     221 2200.75   233.4 2196.42   482.3 2186.45   490.6 2182.31  545.24 2171.01
   547.5 2170.56  647.882171.013     689 2178.48   720.3 2178.03   758.6 2181.78
   774.5 2192.87   782.6 2201.19     799 2202.69   811.3 2213.86   872.6 2247.87
   888.9 2251.22   897.1 2257.88   909.4 2259.61     938 2272.57   954.3 2282.85
     987 2290.81  1007.5 2301.97    1032 2311.05  1051.8 2322.96  1114.1 2347.59
#Mann= 5 ,-1,0
       0      .1       0  545.24    .045       0  647.88    .025       0
  734.12     .06       0  829.46      .1       0
Bank Sta=545.24,647.88
XS Rating Curve= 0 ,0
Exp/Cntr=0.3,0.1

Type RM Length L Ch R = 1 ,1974    ,426,426,426
BEGIN DESCRIPTION:
structure
END DESCRIPTION:
XS GIS Cut Line= 4
2203351.41632077555895.3043034362203220.67753621556371.819251552
2203173.97091561556653.3016419212203104.89933629556980.788488155
#Sta/Elev= 30
       0 2245.46   130.5 2233.07   147.4 2225.97   184.4 2204.51   196.9 2203.51
   209.3 2199.37   230.1 2200.58   296.4 2195.24   470.6 2186.76   487.2 2182.36
   503.6 2181.97  538.362171.384   544.2 2170.56  648.392171.318     682 2177.36
     755 2180.42   787.5  2209.6   811.3 2216.69   848.8 2241.26   869.3 2244.62
   893.8 2257.64   906.1 2259.01   914.2 2264.46   955.1 2280.25   971.5 2284.03
  1008.3 2303.25  1028.7 2308.52  1045.1 2320.53  1098.2 2347.51  1114.1 2357.85
#Mann= 4 ,-1,0
       0      .1       0  538.36    .045       0  648.39     .06       0
  839.46      .1       0
Bank Sta=538.36,648.39
XS Rating Curve= 0 ,0
Exp/Cntr=0.3,0.1

Type RM Length L Ch R = 1 ,1548    ,532.7,532.7,532.7
XS GIS Cut Line= 3
2202785.81880011555760.569187291     2202776.609      556471.239
     2202769.703      556926.187
#Sta/Elev= 30
       0 2272.33    53.6 2244.81    85.2 2220.71   104.6 2203.39   120.7 2193.51
   128.6 2190.84   152.6 2191.84   217.8 2188.11   266.8 2190.16   372.6 2188.01
   440.6    2184   560.7 2184.19   616.7 2177.96   644.7 2169.62   648.7 2168.05
   760.4    2168  767.142169.922   780.7 2176.24   816.7 2178.74   835.2    2194
   852.7  2203.8   868.7 2217.08   884.7 2226.69   896.7 2228.96   948.7 2252.32
   964.7 2261.28   980.7  2264.7   992.5 2271.91  1016.5 2280.88  1165.7 2363.66
#Mann= 5 ,-1,0
       0      .1       0   644.7    .045       0  767.14     .07       0
  850.73     .06       0  950.73      .1       0
Bank Sta=644.7,767.14
XS Rating Curve= 0 ,0
Exp/Cntr=0.3,0.1