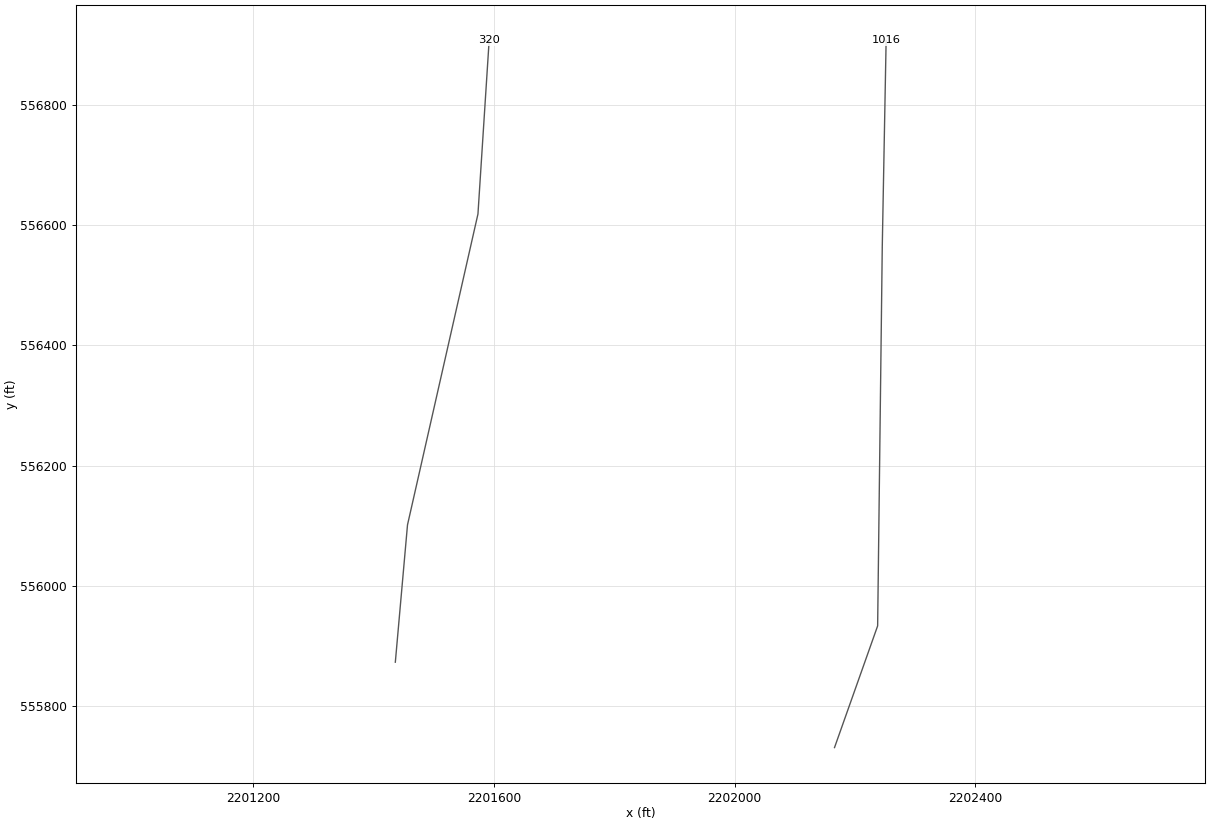
HEC-RAS study ELKRIV.prj: ELKRIV

--- ELKRIV.g01 (geometry) --- (continued)

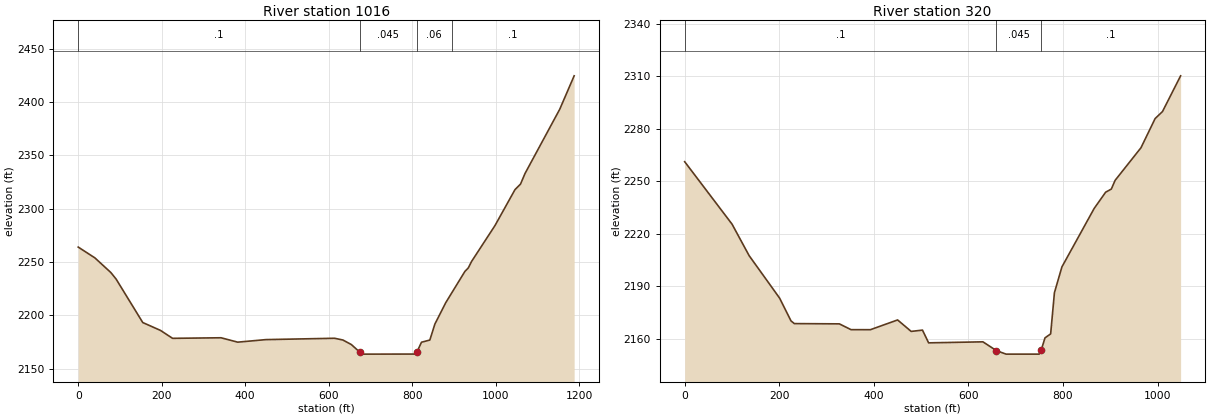
Type RM Length L Ch R = 1 ,1016    ,695.8,695.8,695.8
XS GIS Cut Line= 4
2202165.97409212555731.4876774762202237.64787346555933.710131971
2202245.32720718556563.4154965992202251.76205367556906.739974204
#Sta/Elev= 30
       0 2264.12      40 2253.98    78.2 2240.24    90.8  2234.1   154.6 2193.38
     197 2186.01     226 2178.58     342  2179.1     382 2174.99   449.7 2177.38
     614 2178.64     634 2176.99   654.1 2172.76     675 2165.38   682.1 2163.77
   806.1 2163.82   810.8 2165.43   822.1 2174.93   842.1 2176.96   854.1 2191.89
   880.2 2212.01   926.1 2241.32   934.1 2244.53   942.1 2250.68   998.1  2284.3
  1046.1 2318.03  1059.3 2323.21  1070.1 2333.16  1153.1 2393.27  1187.7 2424.67
#Mann= 4 ,-1,0
       0      .1       0     675    .045       0   810.8     .06       0
   894.3      .1       0
Bank Sta=675,810.8
XS Rating Curve= 0 ,0
Exp/Cntr(USF)=0,0
Exp/Cntr=0.3,0.1

Type RM Length L Ch R = 1 ,320     ,,,
XS GIS Cut Line= 4
2201436.13525099555873.3868098182201456.37306454556101.571789371
 2201573.4514595556618.1611372182201592.11224043556907.403241593
#Sta/Elev= 30
       0 2261.12   100.2 2225.45   136.3 2207.47   200.6 2183.28   224.8 2170.23
   231.9 2168.68   327.1 2168.53   351.7 2165.22   392.7  2165.2   450.2 2170.77
   478.9 2164.22   502.8 2164.96   515.8 2157.69   630.6 2158.27   659.3 2153.23
   679.6 2151.25   749.6 2151.25   753.9 2153.55   761.8 2160.52   773.8  2162.8
   781.8 2186.34   797.6 2201.04   865.8 2234.42   890.1 2243.71   902.1  2245.5
   910.1 2250.47   964.8 2269.09   994.7 2285.74  1010.3 2289.76  1048.6 2310.15
#Mann= 3 ,-1,0
       0      .1       0   659.3    .045       0   753.9      .1       0
Bank Sta=659.3,753.9
XS Rating Curve= 0 ,0
Exp/Cntr(USF)=0,0
Exp/Cntr=0.3,0.1
LCMann Table=0

Chan Stop Cuts=-1
Use User Specified Reach Order=0
Composite Channel Slope=5